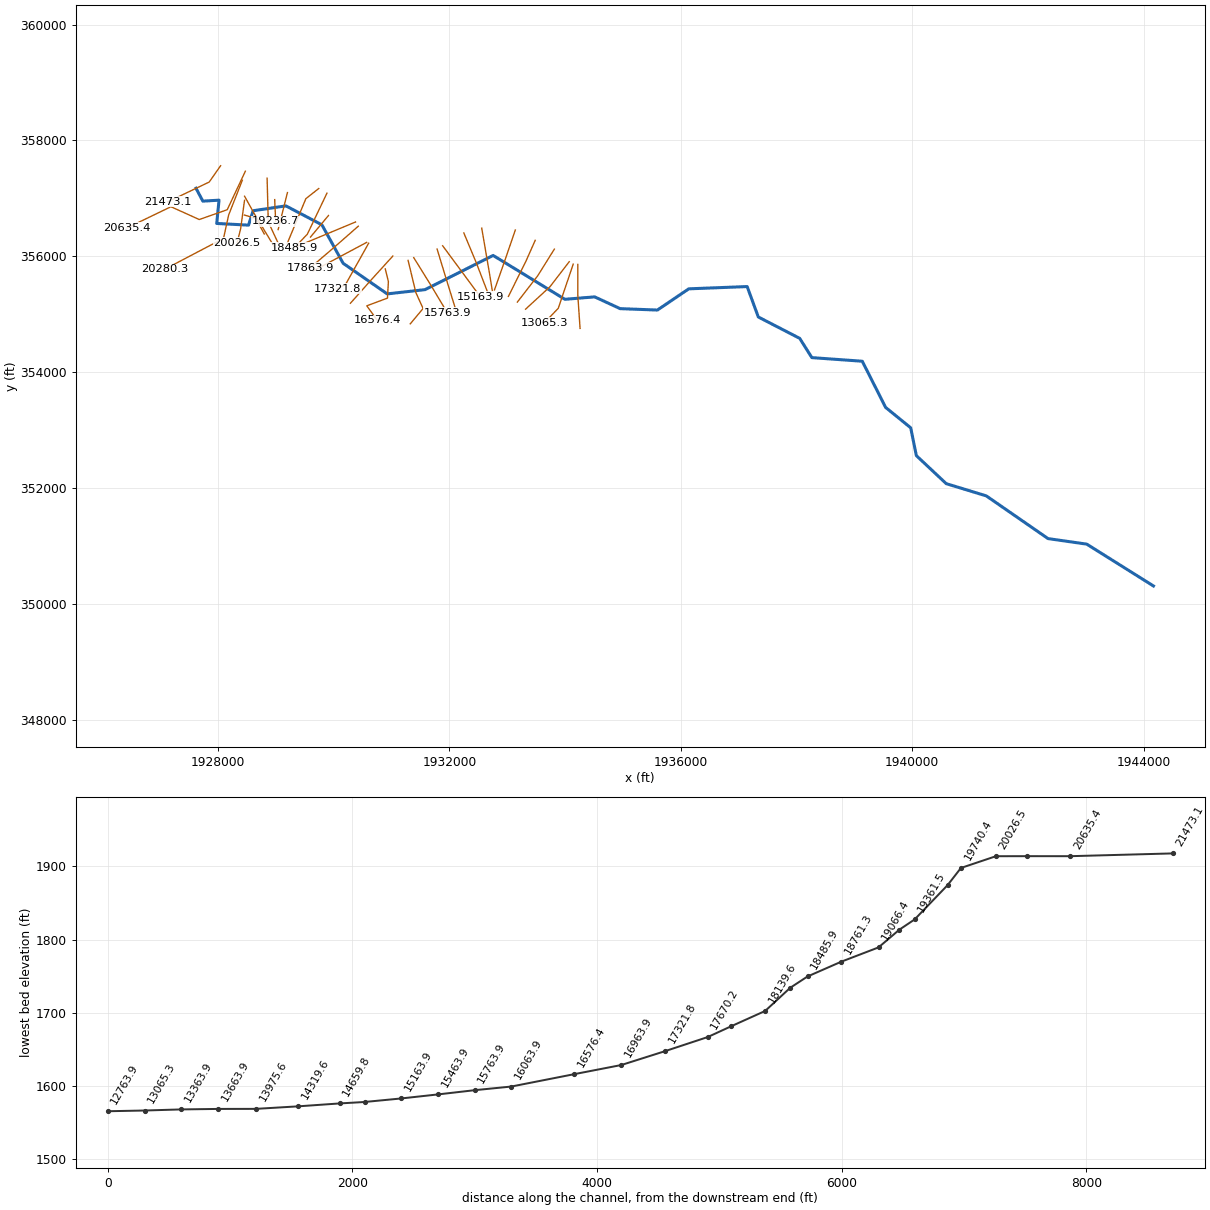
--- ArbckleCrk.prj (project) ---

Proj Title=ArbckleCrk
Current Plan=p01
Default Exp/Contr=0,0
English Units
Geom File=g01
Flow File=f01
Plan File=p01
BEGIN DESCRIPTION:
END DESCRIPTION:
DSS Export Rating Curves= 0
DSS Export Rating Curve Sorted= 0
DSS Export Volume Flow Curves= 0
DXF OffsetX= 0
DXF OffsetY= 0
DXF ScaleX= 0
DXF ScaleY= 0

--- ArbckleCrk.p01 (plan) ---

Plan Title=Floodplain
Program Version=4.00
Geom File=g01
Flow File=f01
K Sum by GR=0
Std Step Tol=0.01
Critical Tol=0.01
Num of Std Step Trials=20
Max Error Tol=0.3
Flow Tol Ratio=0.001
Split Flow NTrial=30
Split Flow Tol=0.02
Split Flow Ratio=0.02
Log Output Level=0
Friction Slope Method=1
Unsteady Friction Slope Method=2
Unsteady Bridges Friction Slope Method=1
Global Log Level=0
CheckData=False
Run HTab=0
Run UNet=0
Run PostProcess=0
UNET Theta=0
UNET Theta Warmup=0
UNET ZTol=0
UNET ZSATol=0
UNET MxIter=0
UNET MaxInSteps=0
UNET DtIC=0
UNET DtMin=0
UNET MaxCRTS=0
UNET WFStab=0
UNET SFStab=0
UNET WFX=0
UNET SFX=0
UNET DSS MLevel=0
UNET DZMax Abort=0
UNET Convert EG Bridges=0
UNET Use Existing IB Tables=0
UNET Froude Limit=0
UNET Froude Power=0
Write IC File=0
Echo Input=False
Echo Output=False
Write Detailed=0

--- ArbckleCrk.f01 (steady flow) ---

Flow Title=NFF Regression Equation
Program Version=4.00
Number of Profiles=1
Profile Names=P100yr
River Rch & RM=ArbckleCrk,Main      ,21473.1
673.6811
River Rch & RM=ArbckleCrk,Main      ,20635.4
679.1160
River Rch & RM=ArbckleCrk,Main      ,20280.3
808.3208
River Rch & RM=ArbckleCrk,Main      ,16576.4
876.7048
River Rch & RM=ArbckleCrk,Main      ,16063.9
985.1789
River Rch & RM=ArbckleCrk,Main      ,14659.8
1010.976
River Rch & RM=ArbckleCrk,Main      ,14319.6
1121.952
River Rch & RM=ArbckleCrk,Main      ,13065.3
1153.812
River Rch & RM=ArbckleCrk,Main      ,8563.9
1277.007
River Rch & RM=ArbckleCrk,Main      ,8272
1531.259
River Rch & RM=ArbckleCrk,Main      ,6163.9
1632.190
Boundary for River Rch & Prof#=ArbckleCrk,Main      ,1
Up Type=0
Dn Type=3
Dn Slope=0.041655

--- ArbckleCrk.g01 (geometry) ---

Geom Title=USGS 3m DEM
Program Version=4.10

River Reach=ArbckleCrk      ,Main
Reach XY= 30
      1927623.77      357172.655     1927741.525        356950.6
     1928021.224      356967.258      1927981.39      356565.636
     1928531.334      356536.153     1928610.203      356784.796
     1929175.854      356868.836     1929798.829      356541.921
     1930165.437      355877.516     1930927.177      355349.259
     1931580.367      355422.655      1932757.74      356012.933
     1933997.034      355255.989     1934512.149      355297.655
     1934951.895       355094.53     1935595.992      355070.225
     1936137.659      355436.544      1937146.99      355475.824
     1937339.048      354950.433      1938054.76      354581.509
     1938264.395      354249.044     1939135.923      354186.544
     1939538.701      353389.669     1939972.729      353037.239
     1940069.907      352556.994     1940587.069      352072.464
     1941278.284      351861.891     1942345.992      351124.044
     1943014.395      351028.558     1944167.147      350306.396

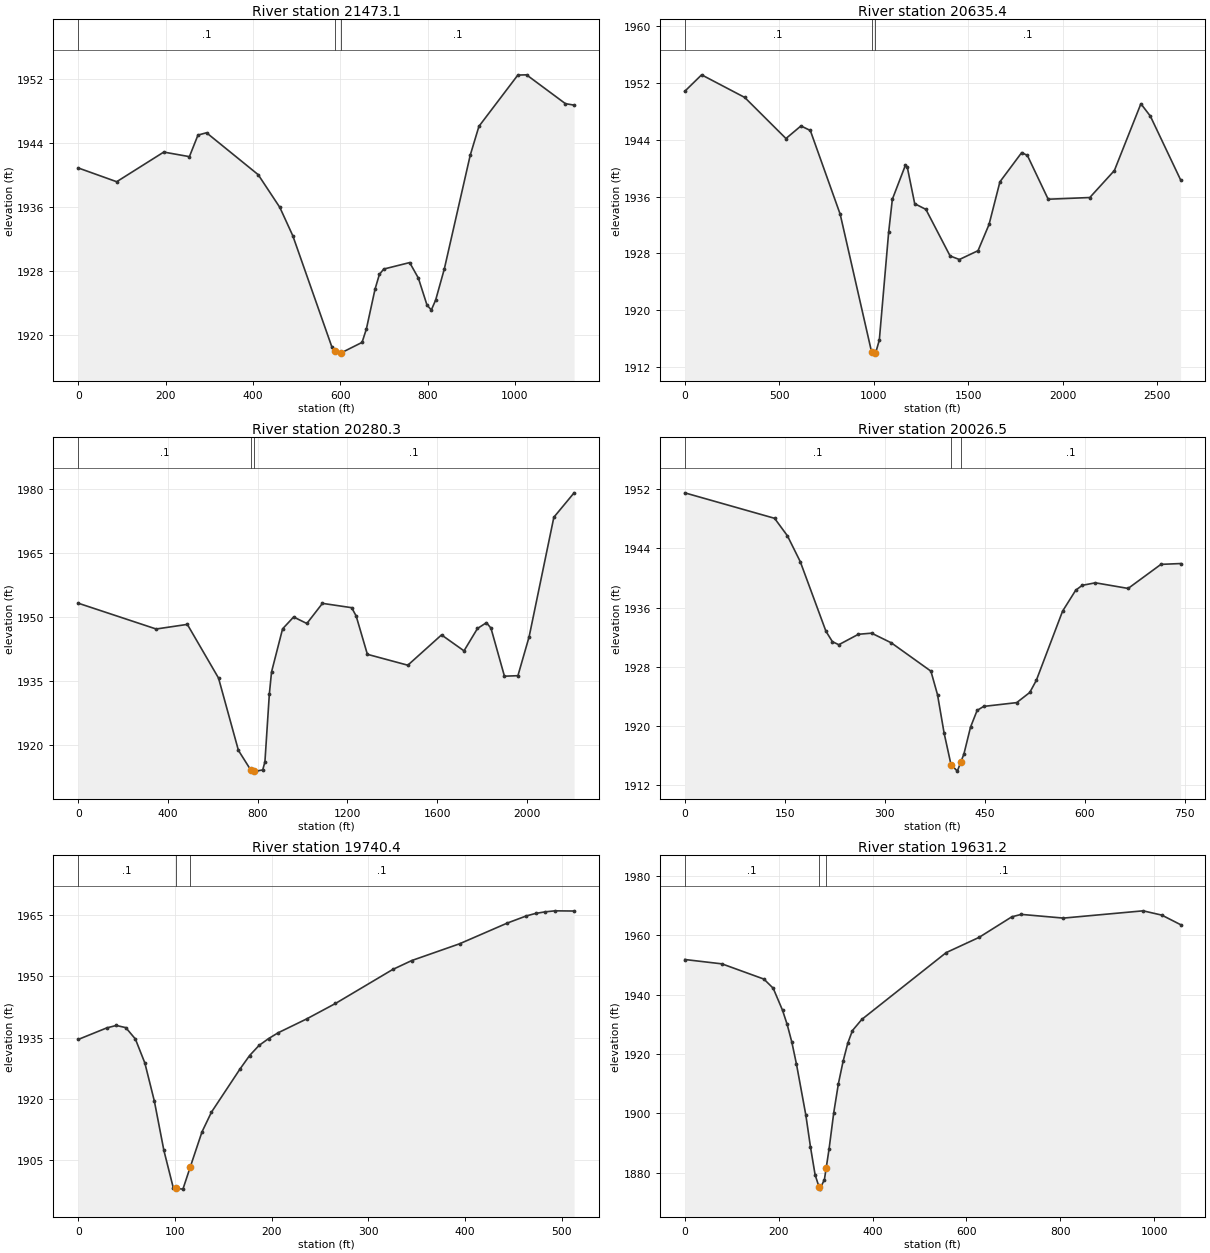
Type RM Length L Ch R = 1 ,21473.1 ,841.5,837.6,824.1
XS GIS Cut Line= 3
     1928048.116      357561.813     1927851.876      357280.778
     1927136.676      356938.962
#Sta/Elev= 30
       0 1940.87    88.1 1939.15   195.9 1942.85   254.6 1942.28   274.2 1944.97
   293.8 1945.26   412.1 1940.03   461.7 1935.94   491.4  1932.4   580.6 1918.56
   587.7 1917.99   600.4 1917.76   602.7 1917.81   649.9  1919.1   659.8 1920.77
   679.7 1925.76   689.6 1927.58   699.5 1928.25   758.9 1929.06   778.8 1927.13
   798.6 1923.76   808.5 1923.14   818.4 1924.38   838.2 1928.25   897.6 1942.46
   917.5 1946.06  1006.6 1952.46  1026.5 1952.49  1115.6 1948.89  1135.4 1948.71
#Mann= 3 , 0 , 0
       0      .1       0   587.7    .045       0   602.7      .1       0
Bank Sta=587.7,602.7
XS Rating Curve= 0 ,0
Exp/Cntr=0.3,0.1

Type RM Length L Ch R = 1 ,20635.4 ,332.3,354.8,376.9
XS GIS Cut Line= 6
      1928476.14      357466.981     1928163.262      356802.955
     1927679.575      356633.057      1927374.28      356771.063
     1927190.607      356854.091     1926432.915      356489.029
#Sta/Elev= 30
       0  1950.8    89.3 1953.12   317.4 1949.94   535.7 1944.16     615 1945.93
   664.6 1945.29   822.8  1933.5   989.4 1914.07  1004.4 1913.98  1010.1 1913.97
  1029.8 1915.81  1079.1 1930.95  1098.8 1935.62  1167.8  1940.4  1177.7 1940.15
  1217.1 1934.99  1276.3 1934.19  1404.4 1927.64  1453.6 1927.14  1552.2 1928.38
  1610.5 1932.07  1668.1 1938.07  1783.3 1942.18  1813.4 1941.78  1923.5 1935.62
  2143.8 1935.86  2273.9 1939.66  2414.1 1949.05  2464.2 1947.31  2624.4 1938.34
#Mann= 3 , 0 , 0
       0      .1       0   989.4    .045       0  1004.4      .1       0
Bank Sta=989.4,1004.4
XS Rating Curve= 0 ,0
Exp/Cntr=0.3,0.1

Type RM Length L Ch R = 1 ,20280.3 ,251.3,253.8,256.8
XS GIS Cut Line= 4
     1928424.021      357311.653     1928187.283      356711.253
     1928098.743      356307.422     1927078.559      355772.355
#Sta/Elev= 30
       0 1953.28   347.5 1947.24   486.5 1948.32   625.5 1935.77   714.3 1918.84
   770.2 1914.18   785.2    1914     793 1913.99   822.6 1914.27   832.4 1916.15
   852.1 1931.99   861.9 1937.19   911.2 1947.28   960.4 1950.05  1019.4 1948.53
  1088.9 1953.24  1219.1 1952.23  1239.1  1950.3  1289.2 1941.32  1469.5 1938.77
  1619.8 1945.86    1720 1942.13    1780 1947.36  1820.1 1948.72  1840.2 1947.44
  1900.3  1936.2  1960.4 1936.32  2010.4 1945.45  2120.6 1973.39  2210.8  1979.1
#Mann= 3 , 0 , 0
       0      .1       0   770.2    .045       0   785.2      .1       0
Bank Sta=770.2,785.2
XS Rating Curve= 0 ,0
Exp/Cntr=0.3,0.1

Type RM Length L Ch R = 1 ,20026.5 ,251.5,285.9,319.1
XS GIS Cut Line= 4
     1928461.786      356964.779     1928429.033      356726.416
     1928394.461      356471.676     1928334.416      356233.312
#Sta/Elev= 30
       0 1951.51   134.7 1948.07     154  1945.7   173.2 1942.22   211.7 1932.82
   221.4 1931.41     231    1931   260.4 1932.41   280.2 1932.56   309.8 1931.25
   369.1 1927.43     379 1924.25   388.9 1919.06   399.2 1914.82   408.7 1913.93
   414.2 1915.22   418.6 1916.25   428.5 1919.87   438.4 1922.13   448.2 1922.67
   497.7 1923.18   517.3 1924.55   527.2  1926.2   566.5 1935.53   586.2 1938.36
     596 1939.02   615.7 1939.36   664.8  1938.6     714 1941.85   743.5 1941.96
#Mann= 3 , 0 , 0
       0      .1       0   399.2    .045       0   414.2      .1       0
Bank Sta=399.2,414.2
XS Rating Curve= 0 ,0
Exp/Cntr=0.3,0.1

Type RM Length L Ch R = 1 ,19740.4 ,127.1,109,91
XS GIS Cut Line= 3
     1928458.702      356710.798     1928657.035      356652.572
     1928802.601      356383.275
#Sta/Elev= 30
       0 1934.54    29.5 1937.37    39.4 1937.97    49.2 1937.44    59.1 1934.66
    68.9 1928.79    78.7 1919.49    88.6 1907.36    98.4 1898.13   100.7 1898.07
   108.3 1897.88   115.7 1903.18     128  1911.9   137.8 1916.74   167.3  1927.3
   177.2 1930.59     187 1933.08   196.9 1934.76   206.7 1936.17   236.3 1939.58
     266 1943.35   325.2 1951.68     345 1953.88   394.3 1957.97   443.7 1963.05
   463.4  1964.8   473.3 1965.43   483.2 1965.81   493.1 1966.05   512.8    1966
#Mann= 3 , 0 , 0
       0      .1       0   100.7    .045       0   115.7      .1       0
Bank Sta=100.7,115.7
XS Rating Curve= 0 ,0
Exp/Cntr=0.3,0.1

Type RM Length L Ch R = 1 ,19631.2 ,280.3,269.6,259
XS GIS Cut Line= 3
     1928462.493      357035.591     1928626.254      356740.821
      1928998.66      356125.806
#Sta/Elev= 30
       0 1951.87    79.3  1950.4   168.6 1945.27   188.4 1942.19   208.3 1934.75
   218.2 1929.96   228.1 1924.02     238 1916.58   257.9 1899.45   267.8 1888.69
   277.7 1879.27   286.4 1875.04   287.6 1874.46   297.5 1877.66   301.4 1881.72
   307.4 1887.97   317.4 1900.24   327.3 1910.02   337.2 1917.49   347.2 1923.64
   357.2 1927.92   377.2 1931.68   556.9  1954.2   626.8 1959.32   696.7 1966.26
   716.7 1967.08   806.5 1965.83   976.3 1968.28  1016.2 1966.83  1056.2 1963.61
#Mann= 3 , 0 , 0
       0      .1       0   286.4    .045       0   301.4      .1       0
Bank Sta=286.4,301.4
XS Rating Curve= 0 ,0
Exp/Cntr=0.3,0.1

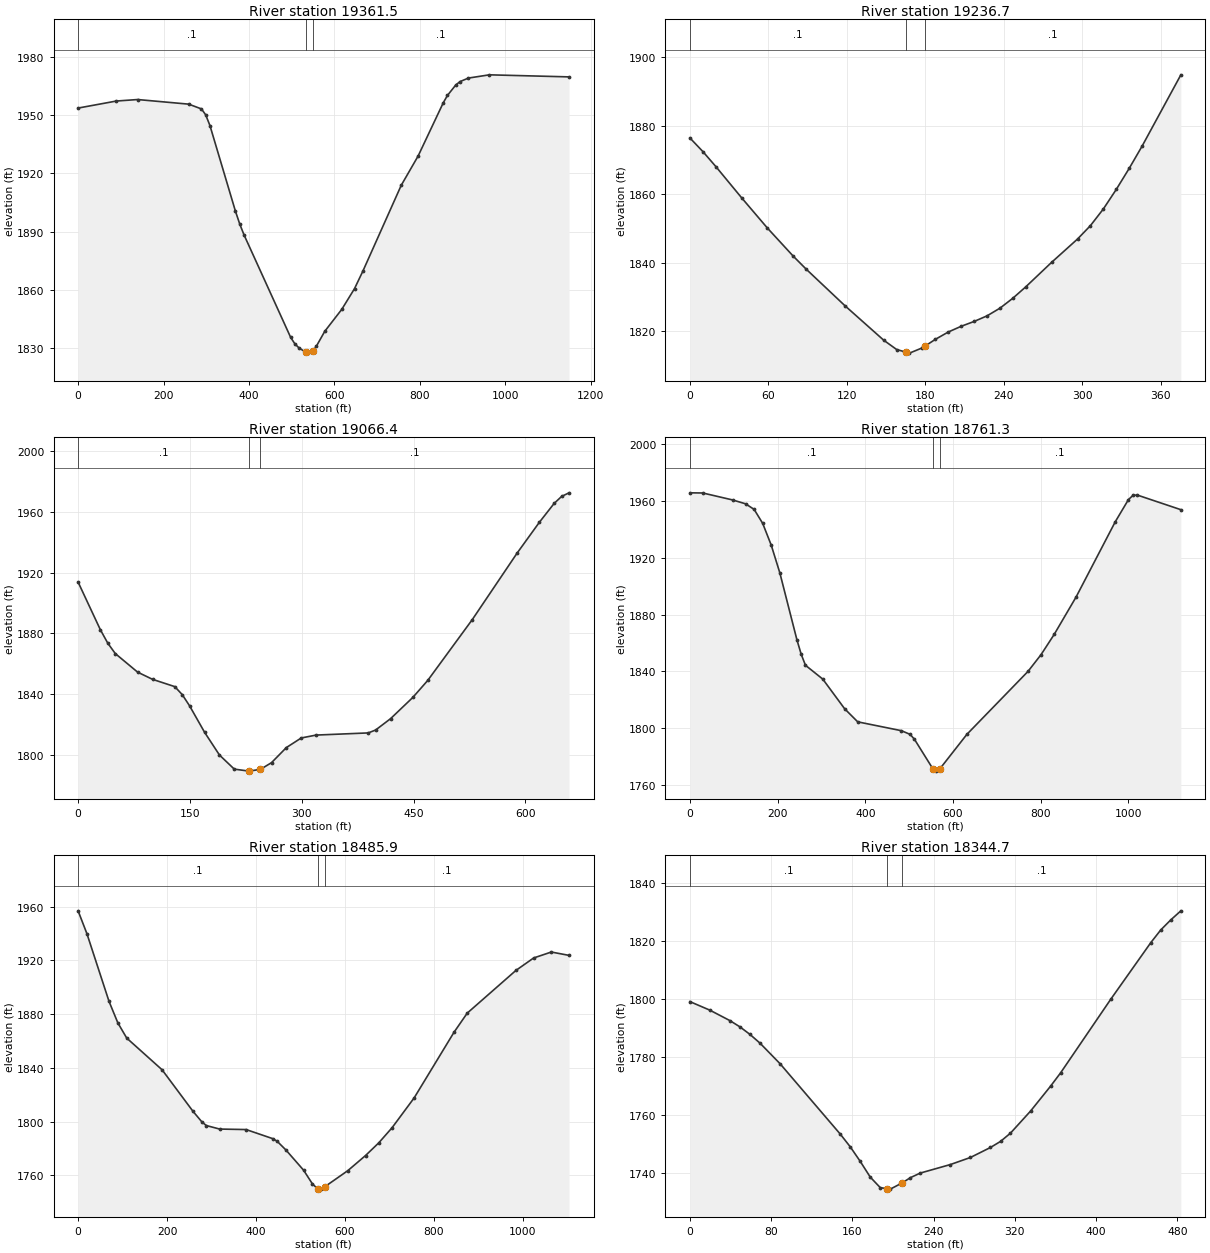
Type RM Length L Ch R = 1 ,19361.5 ,124.5,124.9,125.2
XS GIS Cut Line= 3
     1928851.878      357347.604     1928872.048      356591.161
     1929038.533      356235.512
#Sta/Elev= 30
       0 1953.64    89.6 1957.26   139.4 1958.03   258.9 1955.66   288.8 1953.21
   298.7 1950.18   308.7 1944.65   368.4  1900.6   378.4 1894.05   388.3 1888.51
   497.8 1835.64   507.8  1832.3   517.8 1830.15     534 1827.98   537.7  1827.6
     549 1828.44   557.6 1831.05   577.5 1838.81   617.3  1850.1   647.2 1860.77
   667.1 1869.94   756.7 1913.98     796 1928.94   854.9 1956.33   864.7 1960.13
   884.3 1965.53   894.2 1967.26   913.8 1969.07   962.9 1970.74  1149.4 1969.68
#Mann= 3 , 0 , 0
       0      .1       0     534    .045       0     549      .1       0
Bank Sta=534,549
XS Rating Curve= 0 ,0
Exp/Cntr=0.3,0.1

Type RM Length L Ch R = 1 ,19236.7 ,176.8,170.1,162.5
XS GIS Cut Line= 2
     1928983.193       356976.91     1928999.569      356602.078
#Sta/Elev= 30
       0 1876.39     9.9 1872.42    19.8 1868.05    39.5 1858.94    59.2 1850.11
      79 1841.89    88.9  1838.1   118.5 1827.44   148.1 1817.39     158 1814.67
     165 1813.92   167.8 1813.62   177.7 1815.18     180 1815.75   187.6 1817.65
   197.5 1819.79   207.3 1821.45   217.2 1822.86   227.1  1824.5     237 1826.75
   246.8 1829.64   256.7 1832.97   276.4  1840.1   296.2  1846.9   306.1 1850.82
     316  1855.7   325.8 1861.36   335.7 1867.51   345.6 1874.03   375.2 1894.81
#Mann= 3 , 0 , 0
       0      .1       0     165    .045       0     180      .1       0
Bank Sta=165,180
XS Rating Curve= 0 ,0
Exp/Cntr=0.3,0.1

Type RM Length L Ch R = 1 ,19066.4 ,308.2,305,302.8
XS GIS Cut Line= 2
      1929203.21      357098.821     1929043.088      356460.152
#Sta/Elev= 30
       0 1913.74    29.9 1882.37    39.9  1873.5    49.9 1866.73    79.8 1854.53
    99.8  1849.8   129.7 1844.99   139.7 1839.73   149.6  1832.3   169.6 1815.01
   189.6 1800.02   209.5 1790.75   229.4 1789.44   229.6 1789.45   244.6 1790.62
   259.4    1795   279.3 1804.92   299.3 1811.24   319.2 1813.14   389.1 1814.56
     399 1816.46     419  1823.9   448.9 1837.88   468.9 1849.06   528.7 1889.09
   588.6 1932.66   618.5 1952.96   638.5 1965.48   648.5 1970.06   658.4 1972.41
#Mann= 3 , 0 , 0
       0      .1       0   229.6    .045       0   244.6      .1       0
Bank Sta=229.6,244.6
XS Rating Curve= 0 ,0
Exp/Cntr=0.3,0.1

Type RM Length L Ch R = 1 ,18761.3 ,276.8,275.5,274.1
XS GIS Cut Line= 3
      1929744.01      357168.603     1929521.634      356993.286
     1929199.794      356220.756
#Sta/Elev= 30
       0 1965.67    29.3 1965.56    97.6 1960.64   126.9 1957.95   146.5 1954.01
     166 1944.18   185.5 1928.87   205.1 1909.39   244.1 1862.28   253.9 1852.07
   263.6 1844.36   303.1 1834.63   352.9  1813.8   382.8 1804.57   482.4 1798.35
   502.4 1795.75   512.3 1792.28   554.6 1771.37   562.1  1769.9   569.6 1771.27
   631.9 1795.77   771.4 1840.08   801.2 1851.88   831.1 1866.09     881 1892.36
   970.6 1945.41  1000.5 1960.91  1010.5 1963.79  1020.4 1964.13  1120.1 1953.81
#Mann= 3 , 0 , 0
       0      .1       0   554.6    .045       0   569.6      .1       0
Bank Sta=554.6,569.6
XS Rating Curve= 0 ,0
Exp/Cntr=0.3,0.1

Type RM Length L Ch R = 1 ,18485.9 ,147,141,135
XS GIS Cut Line= 3
     1929886.138      357088.743     1929547.108      356380.091
     1929327.401      356149.555
#Sta/Elev= 30
       0 1956.95    19.9 1939.89    69.6  1889.5    89.5 1873.45   109.4 1862.19
   188.9 1838.59   258.5 1807.62   278.4 1799.78   288.4 1797.08   318.2 1794.46
   377.9 1794.08   437.5 1787.35   447.5 1785.42   467.4 1778.87   507.1 1763.83
     527  1753.6   539.3 1749.78   546.9 1749.73   554.3  1751.4   606.6  1763.5
   646.4 1774.74   676.2  1784.2     706 1795.43   755.7 1817.65   845.3  1866.5
   875.1 1880.78   984.6 1912.58  1024.4 1921.84  1064.2 1926.27    1104 1923.78
#Mann= 3 , 0 , 0
       0      .1       0   539.3    .045       0   554.3      .1       0
Bank Sta=539.3,554.3
XS Rating Curve= 0 ,0
Exp/Cntr=0.3,0.1

Type RM Length L Ch R = 1 ,18344.7 ,215.7,205.2,194.6
XS GIS Cut Line= 2
     1929912.134       356702.61     1929602.352      356331.417
#Sta/Elev= 30
       0 1799.11    19.7 1796.15    39.5 1792.53    49.3 1790.38    59.2 1787.77
    69.1 1784.74    88.8 1777.65     148 1753.38   157.9 1748.96   167.7 1743.95
   177.6  1738.5   187.5 1734.85   194.2 1734.51   197.3 1734.35   209.2 1736.53
   217.1 1738.31   226.9  1739.9   256.5 1742.84   276.3 1745.29     296 1748.74
   305.9 1750.83   315.7 1753.69   335.5 1761.32   355.2 1769.92   365.1 1774.53
   414.4 1799.91   453.9 1819.49   463.7 1823.87   473.6 1827.35   483.5 1830.47
#Mann= 3 , 0 , 0
       0      .1       0   194.2    .045       0   209.2      .1       0
Bank Sta=194.2,209.2
XS Rating Curve= 0 ,0
Exp/Cntr=0.3,0.1

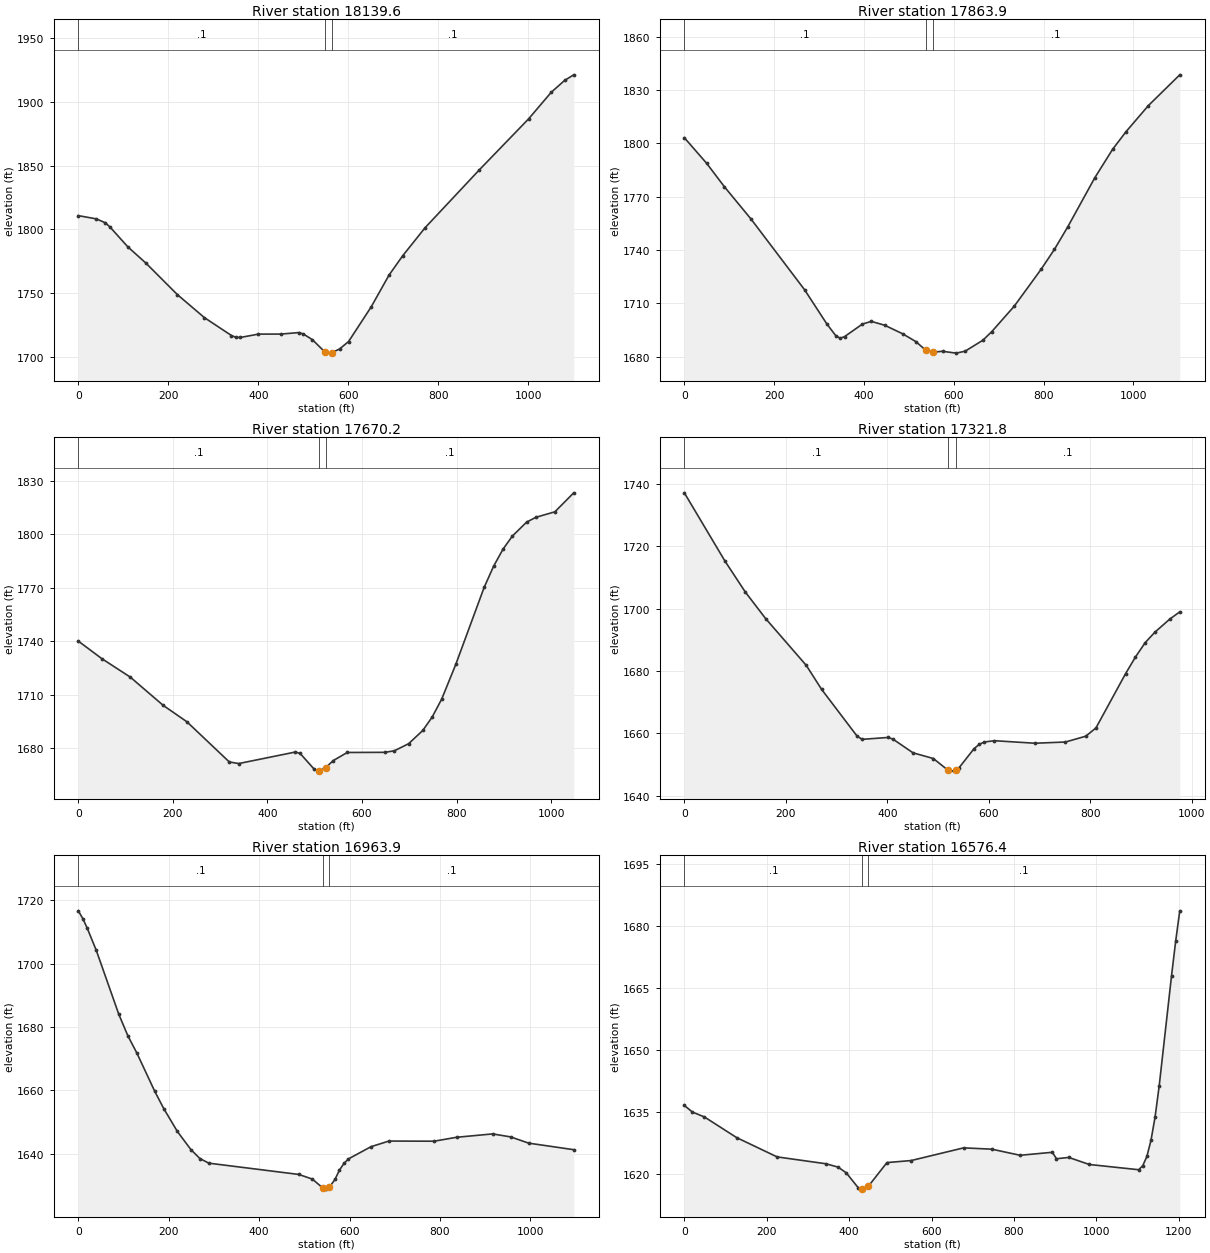
Type RM Length L Ch R = 1 ,18139.6 ,268.4,275.7,282.8
XS GIS Cut Line= 2
     1930379.353      356590.618     1929363.332      356167.201
#Sta/Elev= 30
       0 1810.71      40 1808.17      60 1805.08      70 1801.92   110.1 1786.15
   150.1 1773.44   220.1 1748.66   280.2 1730.56   340.2 1716.53   350.2 1715.08
   360.2    1715   400.3 1717.62   450.3 1717.65   490.3 1718.84   500.3 1717.66
   520.3 1713.18   547.9 1703.55   560.4 1702.68   562.9 1703.06   580.4 1705.93
   600.4 1711.75   650.4 1738.86   690.4 1764.03   720.5 1779.09   770.5 1801.24
   890.6 1846.55  1000.6 1886.79  1050.7 1907.63  1080.7 1917.02  1100.7 1921.34
#Mann= 3 , 0 , 0
       0      .1       0   547.9    .045       0   562.9      .1       0
Bank Sta=547.9,562.9
XS Rating Curve= 0 ,0
Exp/Cntr=0.3,0.1

Type RM Length L Ch R = 1 ,17863.9 ,198.9,193.7,188.8
XS GIS Cut Line= 3
     1930426.735      356517.657     1930016.668       356158.23
     1929592.373      355795.999
#Sta/Elev= 30
       0 1803.19    49.6 1788.81    89.2 1775.59   148.7 1757.35   267.7 1717.64
   317.3 1698.39   337.1 1691.81     347 1690.31   356.9 1691.27   396.6 1698.31
   416.4 1699.82   446.2 1697.64   485.8 1692.88   515.6 1688.44   537.8 1683.53
   552.8 1682.52   575.2 1682.98   605.1 1681.95     625 1683.01   664.8 1689.21
   684.8 1694.11   734.6 1708.36   794.4 1729.12   824.2 1740.37   854.1 1753.16
   913.9 1780.61   953.7 1796.68   983.6  1806.6  1033.4  1821.3  1103.2 1838.58
#Mann= 3 , 0 , 0
       0      .1       0   537.8    .045       0   552.8      .1       0
Bank Sta=537.8,552.8
XS Rating Curve= 0 ,0
Exp/Cntr=0.3,0.1

Type RM Length L Ch R = 1 ,17670.2 ,335.7,348.5,361.3
XS GIS Cut Line= 2
     1930571.526      356238.165     1929647.185      355745.061
#Sta/Elev= 30
       0 1739.97    49.9  1730.1   109.8  1719.8   179.6 1703.91   229.5 1694.76
   319.3  1672.2   339.2 1671.31     459 1677.77     469    1677   498.9 1668.11
     508 1667.15   508.9 1667.06     523 1668.96   538.8 1672.92   568.7 1677.52
   648.5  1677.6   668.5 1678.49   698.4 1682.43   728.4 1689.86   748.3  1697.4
   768.3 1707.41   798.2 1726.91   858.1 1770.04     878 1781.88     898 1791.51
   917.9 1798.88   947.9 1806.67   967.8 1809.41  1007.7 1812.46  1047.6 1823.11
#Mann= 3 , 0 , 0
       0      .1       0     508    .045       0     523      .1       0
Bank Sta=508,523
XS Rating Curve= 0 ,0
Exp/Cntr=0.3,0.1

Type RM Length L Ch R = 1 ,17321.8 ,362.7,357.7,352.9
XS GIS Cut Line= 3
     1930606.098      356223.608     1930209.432      355515.795
     1930063.866      355437.554
#Sta/Elev= 30
       0 1737.11    80.1 1715.21   120.2 1705.29   160.3 1696.76   240.4 1681.75
   270.5 1674.08   340.6 1659.04   350.6 1658.03   400.7 1658.62   410.7 1658.16
   450.8  1653.7   490.8 1651.88   520.4 1648.04   530.9 1647.83   535.4 1648.26
   540.9 1648.78     571 1655.02     581 1656.38     591 1657.16     611 1657.59
   691.2 1656.78   751.3 1657.17   791.4 1659.04   811.4 1661.69   869.7 1679.07
   889.2 1684.42   908.6 1689.08     928 1692.47   957.2 1696.64   976.6 1698.92
#Mann= 3 , 0 , 0
       0      .1       0   520.4    .045       0   535.4      .1       0
Bank Sta=520.4,535.4
XS Rating Curve= 0 ,0
Exp/Cntr=0.3,0.1

Type RM Length L Ch R = 1 ,16963.9 ,371.8,387.4,402.9
XS GIS Cut Line= 3
     1931024.635      356003.146     1930656.263      355597.684
     1930291.991      355187.919
#Sta/Elev= 30
       0 1716.69      10 1714.24    19.9 1711.15    39.8  1704.2    89.6 1684.04
   109.6 1677.27   129.5 1671.83   169.3 1659.69   189.2 1654.25   219.1 1647.09
     249 1641.37   268.9 1638.54   288.8 1637.07     488 1633.51   517.9 1632.04
   540.3 1629.32   547.8 1628.88   555.3 1629.48   567.8 1631.92   577.7 1634.87
   587.7 1636.98   597.6 1638.41   647.5 1642.27   687.4 1644.05   787.1    1644
   836.9 1645.24   916.6  1646.3   956.5 1645.36   996.4 1643.39  1096.1 1641.32
#Mann= 3 , 0 , 0
       0      .1       0   540.3    .045       0   555.3      .1       0
Bank Sta=540.3,555.3
XS Rating Curve= 0 ,0
Exp/Cntr=0.3,0.1

Type RM Length L Ch R = 1 ,16576.4 ,505.4,512.3,523.4
XS GIS Cut Line= 5
     1930893.742      355780.846     1930947.552       355562.31
     1930931.925      355276.427     1930574.265      355143.442
     1930755.505      354893.048
#Sta/Elev= 30
       0  1636.6    19.6    1635    48.9  1633.8   127.2 1628.79   225.1 1624.13
   343.5 1622.47   373.2 1621.65   392.9 1620.27   422.5 1616.58   431.8 1616.34
   432.4 1616.32   446.8 1617.05   491.6 1622.75   550.5 1623.25   677.7 1626.32
   746.2    1626   814.7 1624.52     893 1625.25   902.9 1623.68   932.8    1624
   982.7 1622.29  1102.4 1621.02  1112.3    1622  1122.3 1624.23  1132.3 1628.15
  1142.2 1633.79  1152.2 1641.34  1182.1    1668  1192.1 1676.35  1202.1 1683.76
#Mann= 3 , 0 , 0
       0      .1       0   431.8    .045       0   446.8      .1       0
Bank Sta=431.8,446.8
XS Rating Curve= 0 ,0
Exp/Cntr=0.3,0.1

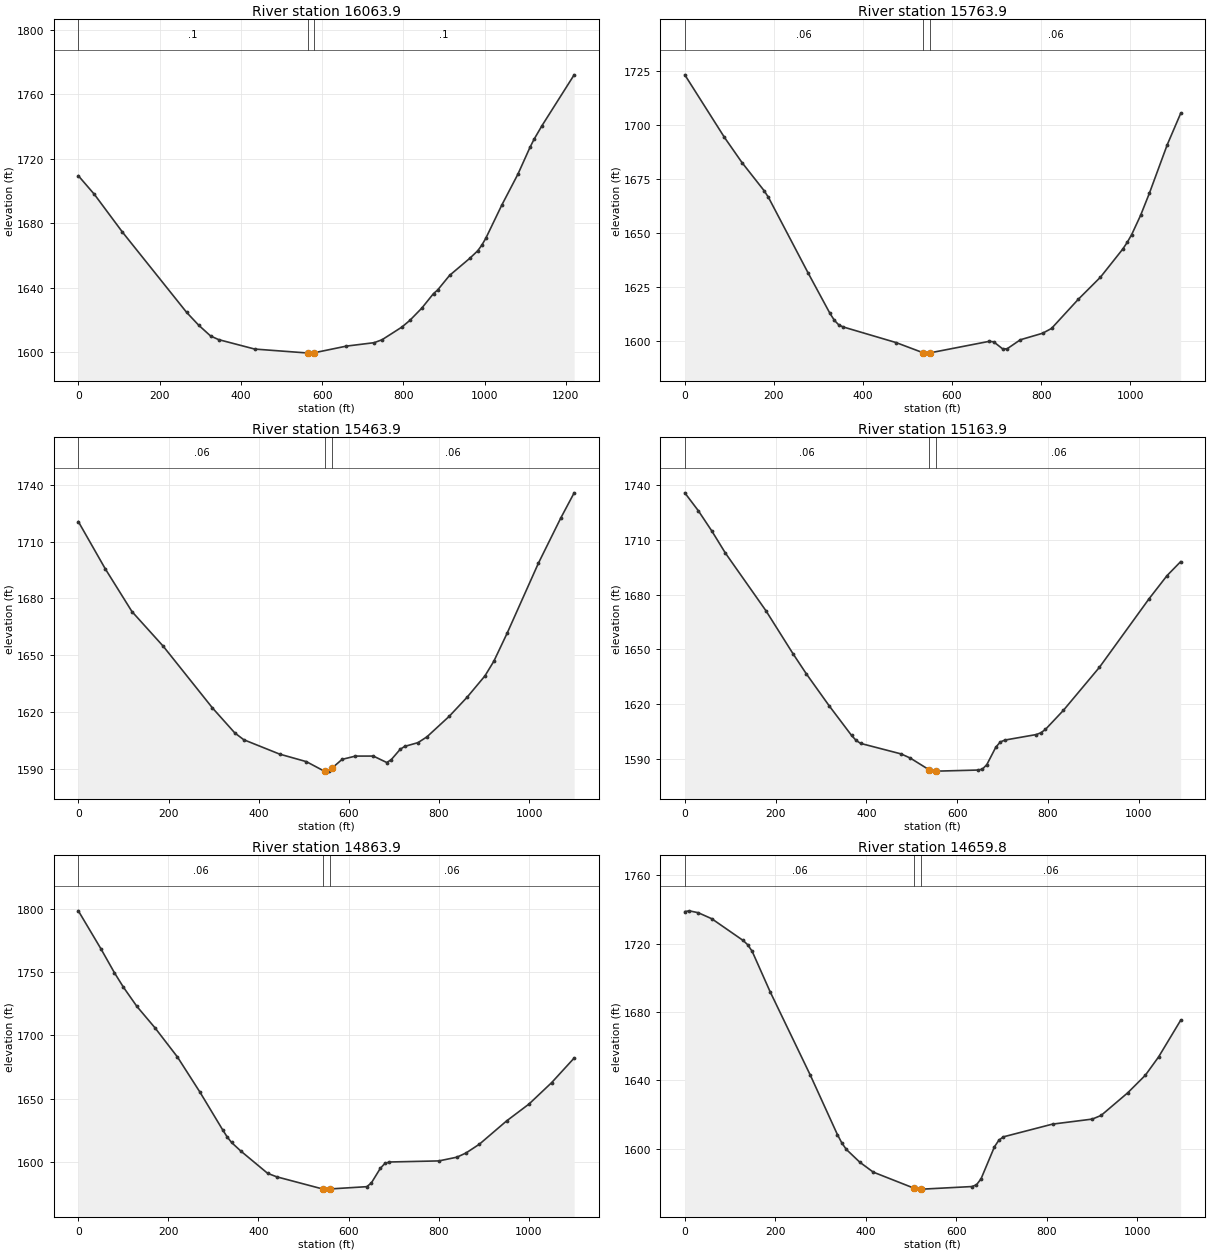
Type RM Length L Ch R = 1 ,16063.9 ,292.7,299.6,302.1
XS GIS Cut Line= 4
     1931287.985      355927.818      1931422.18       355371.62
     1931547.308      355096.789      1931324.98      354831.637
#Sta/Elev= 30
       0  1709.4    39.5 1697.87   108.5 1674.49   266.4 1624.77   295.9 1616.86
   325.5  1610.1   345.3 1607.85     434    1602   564.7 1599.55   572.2 1599.48
   579.7 1599.67   659.8 1603.83     728 1605.95   747.5 1607.78   796.2 1615.62
   815.7 1619.74   844.9 1627.27   874.1 1636.39     884 1638.53   913.7 1647.67
   963.1 1658.18   982.9  1662.9   992.8 1666.34  1002.7 1670.61  1042.2 1691.26
  1081.8 1710.38  1111.4 1726.94  1121.3 1731.91  1141.1 1740.46  1220.2 1771.93
#Mann= 3 , 0 , 0
       0      .1       0   564.7    .045       0   579.7      .1       0
Bank Sta=564.7,579.7
XS Rating Curve= 0 ,0
Exp/Cntr=0.3,0.1

Type RM Length L Ch R = 1 ,15763.9 ,305.8,299.8,294.3
XS GIS Cut Line= 3
     1931385.502      355975.349     1931672.457      355513.889
      1931965.17      355024.973
#Sta/Elev= 30
       0 1723.44    88.9  1694.5   128.4  1682.8   177.8 1669.84   187.7 1666.72
   276.6 1631.75     326 1612.88   335.9 1609.69   345.8 1607.57   355.7 1606.63
   474.2 1599.41   535.9 1594.62   543.4 1594.51   550.9 1594.65   683.4 1599.97
   693.4 1599.75   713.4 1596.52   723.4 1596.48   753.4  1600.7   803.3 1603.72
   823.3 1605.94   883.3 1619.42   933.3 1629.72   983.3 1642.72   993.3 1645.83
  1003.3 1649.43  1023.3 1658.32  1043.3 1668.72  1083.2 1691.07  1113.2 1705.54
#Mann= 3 , 0 , 0
       0     .06       0   535.9    .045       0   550.9     .06       0
#XS Ineff= 2 , 0
                          683.34         1599.93
Permanent Ineff=
       F       F
Bank Sta=535.9,550.9
XS Rating Curve= 0 ,0
Exp/Cntr=0.3,0.1

Type RM Length L Ch R = 1 ,15463.9 ,292.3,300,307.6
XS GIS Cut Line= 3
     1931788.926      356123.394      1931951.34      355592.323
     1932112.685      355072.434
#Sta/Elev= 30
       0 1720.66    59.5 1695.79     119 1673.07   188.4 1654.74   297.5 1622.14
   347.1 1608.92   366.9 1605.34   446.3 1597.75   505.8 1593.75   545.4 1588.74
   547.9  1588.8   555.4 1588.98   562.9 1590.38     585 1594.96   614.7 1596.69
   654.3  1596.7     684  1593.3   693.9 1594.77   713.7 1600.24   723.6 1601.79
   753.3  1603.8   773.1 1606.85   822.6 1617.72   862.2 1627.79   901.8 1639.08
   921.6 1646.85   951.2 1661.73  1020.5 1698.71    1070 1722.53  1099.7 1735.86
#Mann= 3 , 0 , 0
       0     .06       0   547.9    .045       0   562.9     .06       0
Bank Sta=547.9,562.9
XS Rating Curve= 0 ,0
Exp/Cntr=0.3,0.1

Type RM Length L Ch R = 1 ,15163.9 ,305.4,300,293.8
XS GIS Cut Line= 3
     1931885.432      356180.052     1932209.969      355740.972
     1932534.506      355301.892
#Sta/Elev= 30
       0 1735.89    29.8 1726.07    59.6 1714.92    89.4 1702.85   178.7 1671.22
   238.2 1647.68     268 1636.49   317.7 1619.16   367.3  1602.8   377.2 1600.11
   387.2 1598.44   476.5 1592.66   496.4 1590.42   538.5  1583.9   553.5 1583.24
   555.9 1583.23   645.3 1583.82   655.2 1584.28   665.1 1586.77     685 1596.37
   694.9 1599.22   704.8 1600.26   774.3  1603.3   784.2 1604.28   794.2 1606.09
   833.9 1616.59   913.3 1640.22  1022.5 1677.79  1062.2 1690.52    1092 1698.12
#Mann= 3 , 0 , 0
       0     .06       0   538.5    .045       0   553.5     .06       0
Bank Sta=538.5,553.5
XS Rating Curve= 0 ,0
Exp/Cntr=0.3,0.1

Type RM Length L Ch R = 1 ,14863.9 ,209,203.9,199.5
XS GIS Cut Line= 3
     1932251.307      356400.923     1932463.675      355893.055
     1932661.393      355379.196
#Sta/Elev= 30
       0 1798.51      50 1768.58    80.1 1749.59   100.1 1738.13   130.1  1722.9
   170.2 1705.99   220.2 1682.86   270.2 1655.05   320.3 1625.42   330.3 1619.83
   340.3 1615.29   360.3 1608.68   420.4  1590.9   440.4 1588.16     543 1578.48
   550.5  1578.4     558 1578.52   640.6 1580.34   650.6 1583.23   670.6 1594.81
   680.6 1598.67   690.6 1599.86   800.8 1600.72   840.8 1603.68   860.8 1606.96
   890.8 1613.98   950.9  1632.3    1001 1645.75    1051 1662.59  1101.1 1682.07
#Mann= 3 , 0 , 0
       0     .06       0     543    .045       0     558     .06       0
Bank Sta=543,558
XS Rating Curve= 0 ,0
Exp/Cntr=0.3,0.1

Type RM Length L Ch R = 1 ,14659.8 ,351.9,340.2,328.6
XS GIS Cut Line= 3
     1932560.316      356483.806     1932691.325      355721.407
     1932743.553      355403.547
#Sta/Elev= 30
       0 1738.69     9.9 1739.15    29.8 1738.03    59.5 1734.54   128.9 1721.82
   138.8 1719.37   148.8 1715.52   188.4 1691.94   277.7 1642.88   337.2 1608.35
   347.1  1603.4     357 1599.64   386.8 1592.16   416.5 1586.37   507.5 1576.88
   522.5 1576.44   525.6 1576.43   634.7 1577.94   644.6 1578.96   654.6 1582.42
   684.3 1601.19   694.2  1605.1   704.2 1607.01   812.6 1614.44   900.5 1617.38
     920 1619.52   978.6  1632.7  1017.6 1642.98  1046.9 1653.68  1095.7 1675.12
#Mann= 3 , 0 , 0
       0     .06       0   507.5    .045       0   522.5     .06       0
Bank Sta=507.5,522.5
XS Rating Curve= 0 ,0
Exp/Cntr=0.3,0.1

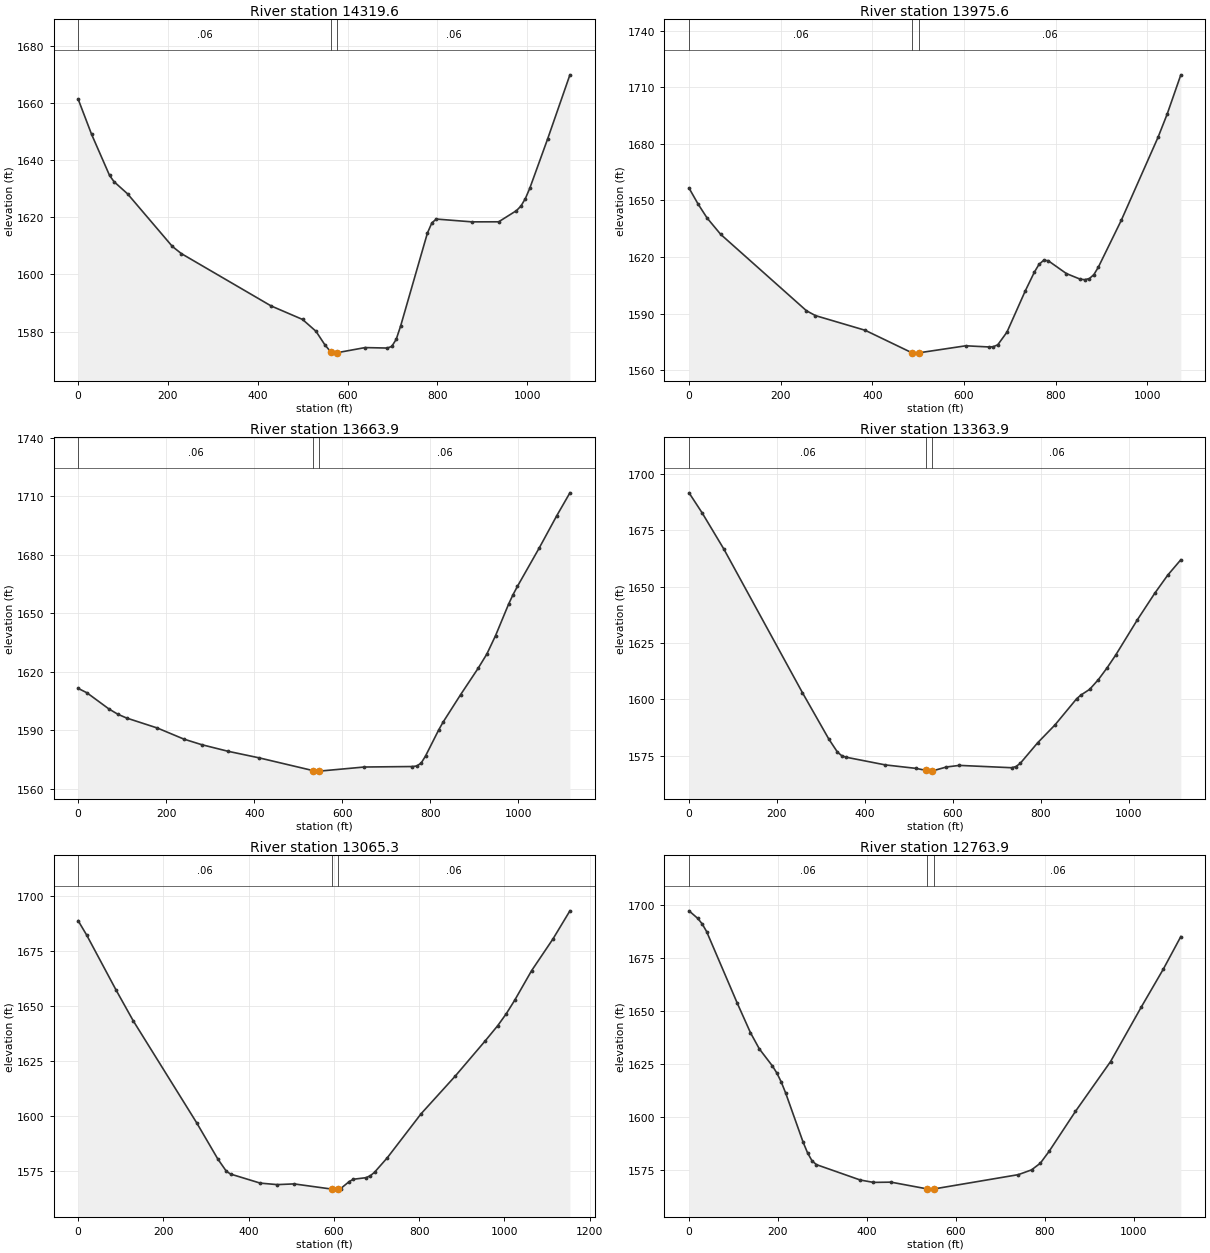
Type RM Length L Ch R = 1 ,14319.6 ,346.8,344,341.2
XS GIS Cut Line= 3
     1933140.823      356452.363     1932962.177       355932.42
     1932780.641      355417.884
#Sta/Elev= 30
       0 1661.42      30 1649.06      70 1634.68      80 1632.48     110 1628.25
   209.9 1609.81   229.9 1607.31   429.8 1588.98   499.8 1584.25   529.8  1580.1
   549.8 1575.31   562.3 1572.97   569.6 1572.45   577.3 1572.61   639.1 1574.39
   688.7 1574.23   698.6 1574.81   708.5 1577.29   718.4 1581.98     778  1614.5
   787.9 1618.06   797.8  1619.4   877.2 1618.42   936.7 1618.44   976.4 1622.36
   986.3 1623.95   996.2 1626.59  1006.1 1630.23  1045.8 1647.48  1095.4 1669.91
#Mann= 3 , 0 , 0
       0     .06       0   562.3    .045       0   577.3     .06       0
Bank Sta=562.3,577.3
XS Rating Curve= 0 ,0
Exp/Cntr=0.3,0.1

Type RM Length L Ch R = 1 ,13975.6 ,313.3,311.2,306.8
XS GIS Cut Line= 3
     1933484.657      356274.556     1933324.535      355914.281
     1933021.712      355306.373
#Sta/Elev= 30
       0 1656.51    19.7 1648.08    39.4 1640.66      69 1632.01   256.3 1591.48
     276  1588.9   384.4 1581.13   486.1 1569.24   494.1 1569.01   501.1 1569.15
     604  1572.9   653.9 1572.29   663.9  1572.4   673.9 1573.44   693.9 1580.14
   733.8 1601.96   753.8 1611.98   763.8 1616.05   773.8 1618.19   783.8 1618.03
   823.7 1611.19   853.7 1608.23   863.7 1607.96   873.7 1608.54   883.6 1610.62
   893.6  1614.7   943.6 1639.53  1023.5 1683.36  1043.4 1695.62  1073.4 1716.57
#Mann= 3 , 0 , 0
       0     .06       0   486.1    .045       0   501.1     .06       0
Bank Sta=486.1,501.1
XS Rating Curve= 0 ,0
Exp/Cntr=0.3,0.1

Type RM Length L Ch R = 1 ,13663.9 ,302.2,300.1,296.2
XS GIS Cut Line= 3
     1933815.157      356122.039     1933528.662       355663.61
     1933175.858      355207.878
#Sta/Elev= 30
       0 1611.42      20 1609.14    70.1 1600.82    90.1 1598.15   110.1 1596.19
   180.2 1591.04   240.3 1585.36   280.3 1582.53   340.4 1579.12   410.4 1575.78
   533.1 1569.22   540.6 1568.93   548.1 1568.94   649.9 1571.04   759.2 1571.29
   769.1 1571.57   779.1 1573.08     789 1576.71   818.8 1590.04   828.8 1594.07
   868.5 1608.14   908.2 1621.64   928.1 1628.98     948 1638.49   977.8 1654.74
   987.8 1659.56   997.7 1663.78  1047.4 1683.57  1087.1 1700.08  1116.9 1711.79
#Mann= 3 , 0 , 0
       0     .06       0   533.1    .045       0   548.1     .06       0
Bank Sta=533.1,548.1
XS Rating Curve= 0 ,0
Exp/Cntr=0.3,0.1

Type RM Length L Ch R = 1 ,13363.9 ,290.9,298.4,309.9
XS GIS Cut Line= 3
     1934072.513      355905.195     1933739.303      355472.812
     1933317.941      355085.274
#Sta/Elev= 30
       0 1691.56    29.8 1682.68    79.4 1666.57     258 1602.98   317.6 1582.56
   337.4 1576.72   347.4 1575.06   357.3 1574.42   446.6 1571.01   516.1 1569.48
   538.4 1568.61   545.9 1568.26   553.4 1568.34   585.4  1570.1     615  1570.8
   733.4 1569.77   743.3 1570.27   753.2  1571.7   792.6 1580.78   832.1 1588.71
   881.5 1600.34   891.3 1601.98   911.1  1604.5   930.8 1608.78   950.6 1613.99
   970.3 1619.69  1019.6 1635.32  1059.1 1647.06  1088.8 1655.14  1118.4 1661.91
#Mann= 3 , 0 , 0
       0     .06       0   538.4    .045       0   553.4     .06       0
Bank Sta=538.4,553.4
XS Rating Curve= 0 ,0
Exp/Cntr=0.3,0.1

Type RM Length L Ch R = 1 ,13065.3 ,293.8,301.4,310.5
XS GIS Cut Line= 3
     1934140.936      355863.073     1933883.143      355100.933
     1933641.705      354848.878
#Sta/Elev= 30
       0 1688.63    19.9 1682.14    89.4    1657   129.1 1643.23   278.1 1596.87
   327.8 1580.41   347.6  1574.9   357.6 1573.61   427.1  1569.5   466.8 1568.82
   506.6 1569.14   594.4  1566.8   605.9 1566.77   609.4 1566.85   615.8 1567.01
   635.7 1570.18   645.6 1571.25   675.4 1571.97   685.4 1572.85   695.3 1574.43
   725.1 1580.98   804.6 1601.01   884.3 1618.02   954.1 1633.88   984.1 1640.94
    1004  1646.3    1024  1652.5  1063.8 1665.97  1113.7  1680.3  1153.6  1693.1
#Mann= 3 , 0 , 0
       0     .06       0   594.4    .045       0   609.4     .06       0
Bank Sta=594.4,609.4
XS Rating Curve= 0 ,0
Exp/Cntr=0.3,0.1

Type RM Length L Ch R = 1 ,12763.9 ,303.4,299.7,291.4
XS GIS Cut Line= 3
     1934220.417      355858.034     1934221.034      355315.016
      1934259.64      354753.438
#Sta/Elev= 30
       0 1697.06    19.8 1693.45    29.6 1690.88    39.5 1687.29   108.6 1653.43
   138.2 1639.55     158 1631.96   187.6 1623.85   197.5 1620.54   207.3 1616.34
   217.2 1611.16   256.7 1587.84   266.6 1582.86   276.4  1579.2   286.3 1577.35
     385 1570.08   414.7 1568.96   454.2 1569.07   535.5 1565.89     543 1565.78
   550.5 1565.86   740.5 1572.61   770.2 1574.86   789.9    1578   809.7  1583.6
   868.9 1602.44   947.9 1625.96    1017 1651.69  1066.4 1669.52  1105.9 1684.92
#Mann= 3 , 0 , 0
       0     .06       0   535.5    .045       0   550.5     .06       0
Bank Sta=535.5,550.5
XS Rating Curve= 0 ,0
Exp/Cntr=0.3,0.1