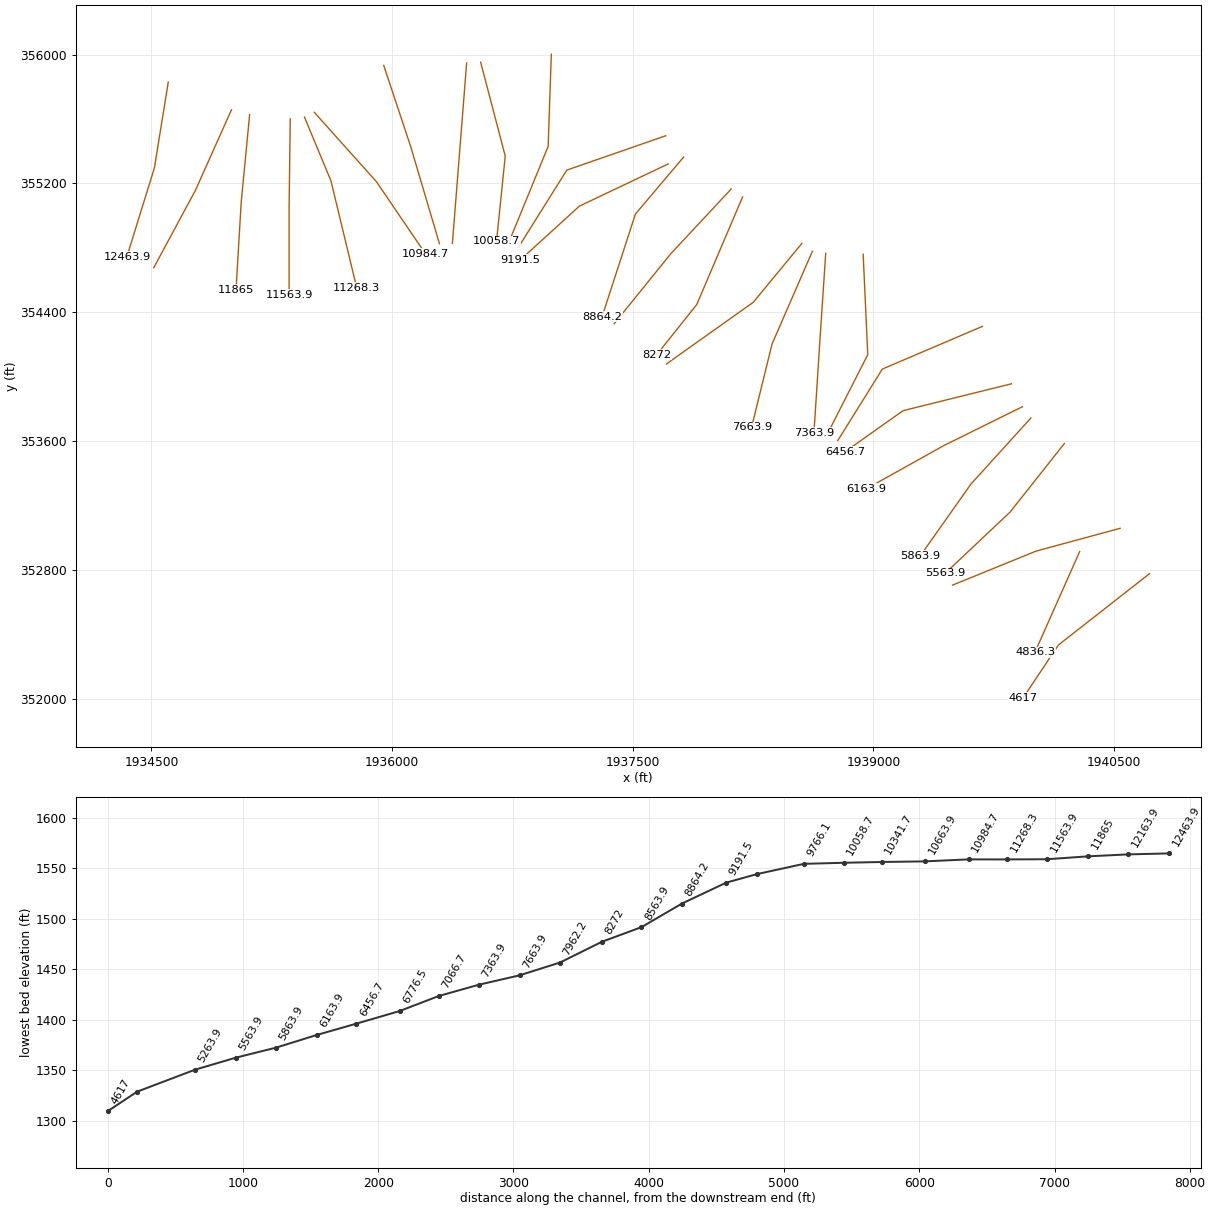
HEC-RAS study ArbckleCrk.prj: ArbckleCrk

--- ArbckleCrk.g01 (geometry) --- (continued)

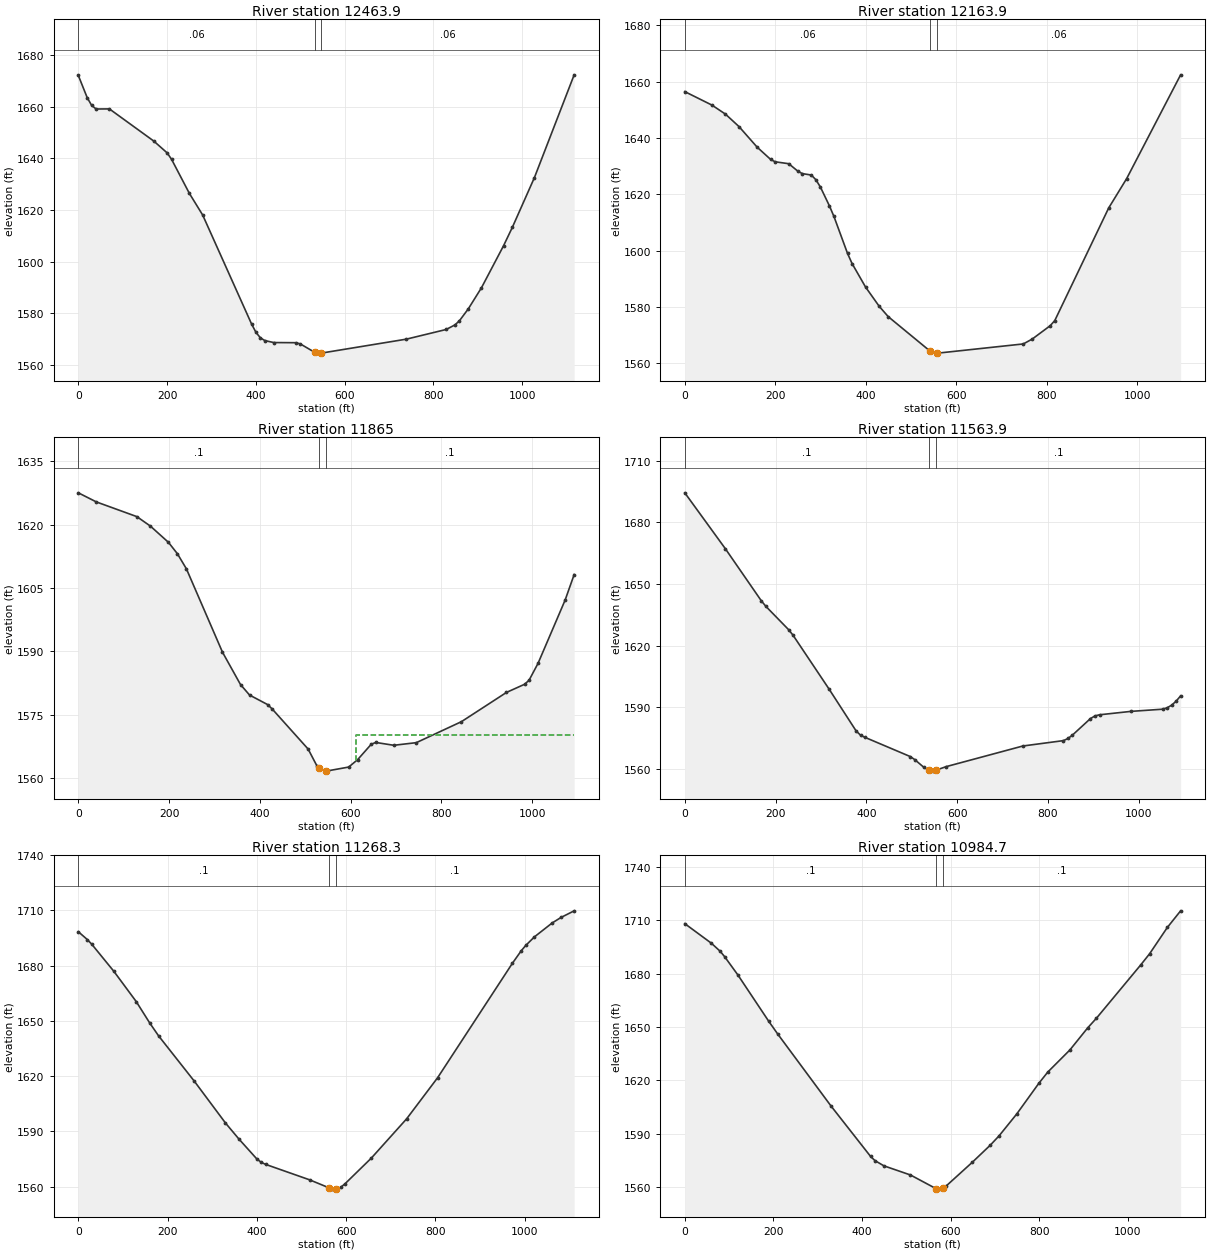
Type RM Length L Ch R = 1 ,12463.9 ,306,300,295.5
XS GIS Cut Line= 3
      1934604.84      355829.914      1934518.28      355296.471
     1934346.986      354745.631
#Sta/Elev= 30
       0    1672      20 1663.41      30 1660.44      40 1659.03      70 1659.07
   170.1 1646.62   200.2 1642.05   210.2 1639.54   250.2  1626.4   280.2 1618.03
   390.3 1575.91   400.3 1572.64   410.3 1570.53   420.3 1569.48   440.3 1568.71
   490.4 1568.65   500.4 1568.17   532.9  1564.9   540.4 1564.62   547.9 1564.64
   739.3 1570.03   828.8 1573.76   848.7 1575.54   858.7 1577.12   878.6  1581.7
   908.4 1589.89   958.2 1606.15     978 1613.26  1027.8 1632.52  1117.3 1672.25
#Mann= 3 , 0 , 0
       0     .06       0   532.9    .045       0   547.9     .06       0
Bank Sta=532.9,547.9
XS Rating Curve= 0 ,0
Exp/Cntr=0.3,0.1

Type RM Length L Ch R = 1 ,12163.9 ,291.4,298.8,308.4
XS GIS Cut Line= 3
     1934998.772       355657.53     1934773.679      355156.565
     1934513.835       354676.13
#Sta/Elev= 30
       0 1656.47    59.9 1651.69    89.9 1648.47   119.8 1644.05   159.8 1636.76
   189.7 1632.39   199.7 1631.56   229.7 1630.88   249.6 1628.25   259.6 1627.37
   279.6 1626.86   289.6 1625.19   299.6  1622.6   319.5 1615.92   329.5 1612.16
   359.5 1599.04   369.5 1595.46   399.4 1587.09   429.4 1580.29   449.4  1576.6
   541.7 1564.39   556.7 1563.68   559.1 1563.65   747.8 1566.91   767.7 1568.66
   807.4  1573.4   817.4 1575.21   936.5 1615.18   976.2  1625.6  1095.4 1662.43
#Mann= 3 , 0 , 0
       0     .06       0   541.7    .045       0   556.7     .06       0
Bank Sta=541.7,556.7
XS Rating Curve= 0 ,0
Exp/Cntr=0.3,0.1

Type RM Length L Ch R = 1 ,11865   ,299.2,301.1,302.7
XS GIS Cut Line= 3
     1935112.081      355628.053     1935059.496      355084.671
     1935027.025      354539.182
#Sta/Elev= 30
       0 1627.51    39.7 1625.36     129 1621.88   158.8 1619.64   198.5 1615.81
   218.4 1613.09   238.2 1609.52   317.6 1589.83   357.3 1582.18   377.2  1579.7
   416.9 1577.45   426.8 1576.44   506.2 1566.94   526.1 1562.86     531  1562.4
   545.9 1561.71     546 1561.71   595.6 1562.67   615.5 1564.44   645.3 1568.06
   655.2 1568.49     695 1567.82   744.6 1568.44     844  1573.4   943.3 1580.32
   983.1 1582.24     993 1583.19  1012.9 1587.21  1072.5 1602.15  1092.4 1608.19
#Mann= 3 , 0 , 0
       0      .1       0     531    .045       0     546      .1       0
#XS Ineff= 2 , 0
                          612.41         1570.18
Permanent Ineff=
       F       F
Bank Sta=531,546
XS Rating Curve= 0 ,0
Exp/Cntr=0.3,0.1

Type RM Length L Ch R = 1 ,11563.9 ,289.8,295.5,300.8
XS GIS Cut Line= 3
     1935365.274       355600.61     1935358.001        355054.6
     1935358.001       354508.61
#Sta/Elev= 30
       0 1694.39    89.4 1667.15   168.8 1641.72   178.7 1639.07   228.4  1627.8
   238.3 1625.08   317.7 1598.83   377.3 1578.44   387.2 1576.33   397.1 1575.28
   496.4 1565.97   506.4 1564.48   526.2 1560.76   538.6 1559.17   546.1 1558.86
   553.6 1559.35   575.8 1561.06   744.6  1571.1     834 1573.72   843.9 1574.76
   853.8 1576.42   893.5 1584.47   903.4 1585.74   913.4  1586.3   982.8 1587.96
  1052.3 1589.02  1062.3  1589.7  1072.2 1590.99  1082.1 1592.92    1092 1595.52
#Mann= 3 , 0 , 0
       0      .1       0   538.6    .045       0   553.6      .1       0
Bank Sta=538.6,553.6
XS Rating Curve= 0 ,0
Exp/Cntr=0.3,0.1

Type RM Length L Ch R = 1 ,11268.3 ,272.6,283.8,292.3
XS GIS Cut Line= 3
     1935453.907      355612.221     1935619.012      355215.566
     1935779.193       354553.16
#Sta/Elev= 30
       0 1698.44      20 1694.22      30 1691.68    79.9 1676.85   129.9 1660.46
   159.9 1648.92   179.8 1641.91   259.8 1617.32   329.7 1594.59   359.7 1585.92
   399.7 1575.14   409.7 1573.24   419.6 1572.12   518.5  1563.7   561.3 1559.43
   567.9 1558.84   576.3  1558.7   577.8 1558.67   587.7  1559.6   597.6 1561.57
   656.8 1575.57   735.8 1596.88     805 1619.12   972.9 1681.38   992.6 1688.13
  1002.5 1690.97  1022.2 1695.67  1061.8 1703.19  1081.5 1706.17  1111.1 1709.79
#Mann= 3 , 0 , 0
       0      .1       0   561.3    .045       0   576.3      .1       0
Bank Sta=561.3,576.3
XS Rating Curve= 0 ,0
Exp/Cntr=0.3,0.1

Type RM Length L Ch R = 1 ,10984.7 ,329.8,320.6,313.2
XS GIS Cut Line= 3
     1935515.125      355641.653     1935902.613      355210.759
     1936207.055      354764.649
#Sta/Elev= 30
       0 1708.15      60 1697.14    79.9  1692.6    89.9 1689.58   119.9 1679.26
   189.8  1653.1   209.8 1646.04   329.7 1605.66   419.6 1577.09   429.6 1574.74
   449.6 1571.83   509.6 1566.68   567.9 1558.91   569.5 1558.72   579.5 1558.76
   582.9 1559.29   589.5 1560.33   649.5  1573.9   689.5 1583.39   709.5 1588.67
   749.5 1601.01   799.5  1618.3   819.5 1624.58   869.6 1637.07   909.6 1649.44
   929.6 1654.95  1029.6 1684.95  1049.6 1691.22  1089.6 1706.01  1119.6 1715.37
#Mann= 3 , 0 , 0
       0      .1       0   567.9    .045       0   582.9      .1       0
Bank Sta=567.9,582.9
XS Rating Curve= 0 ,0
Exp/Cntr=0.3,0.1

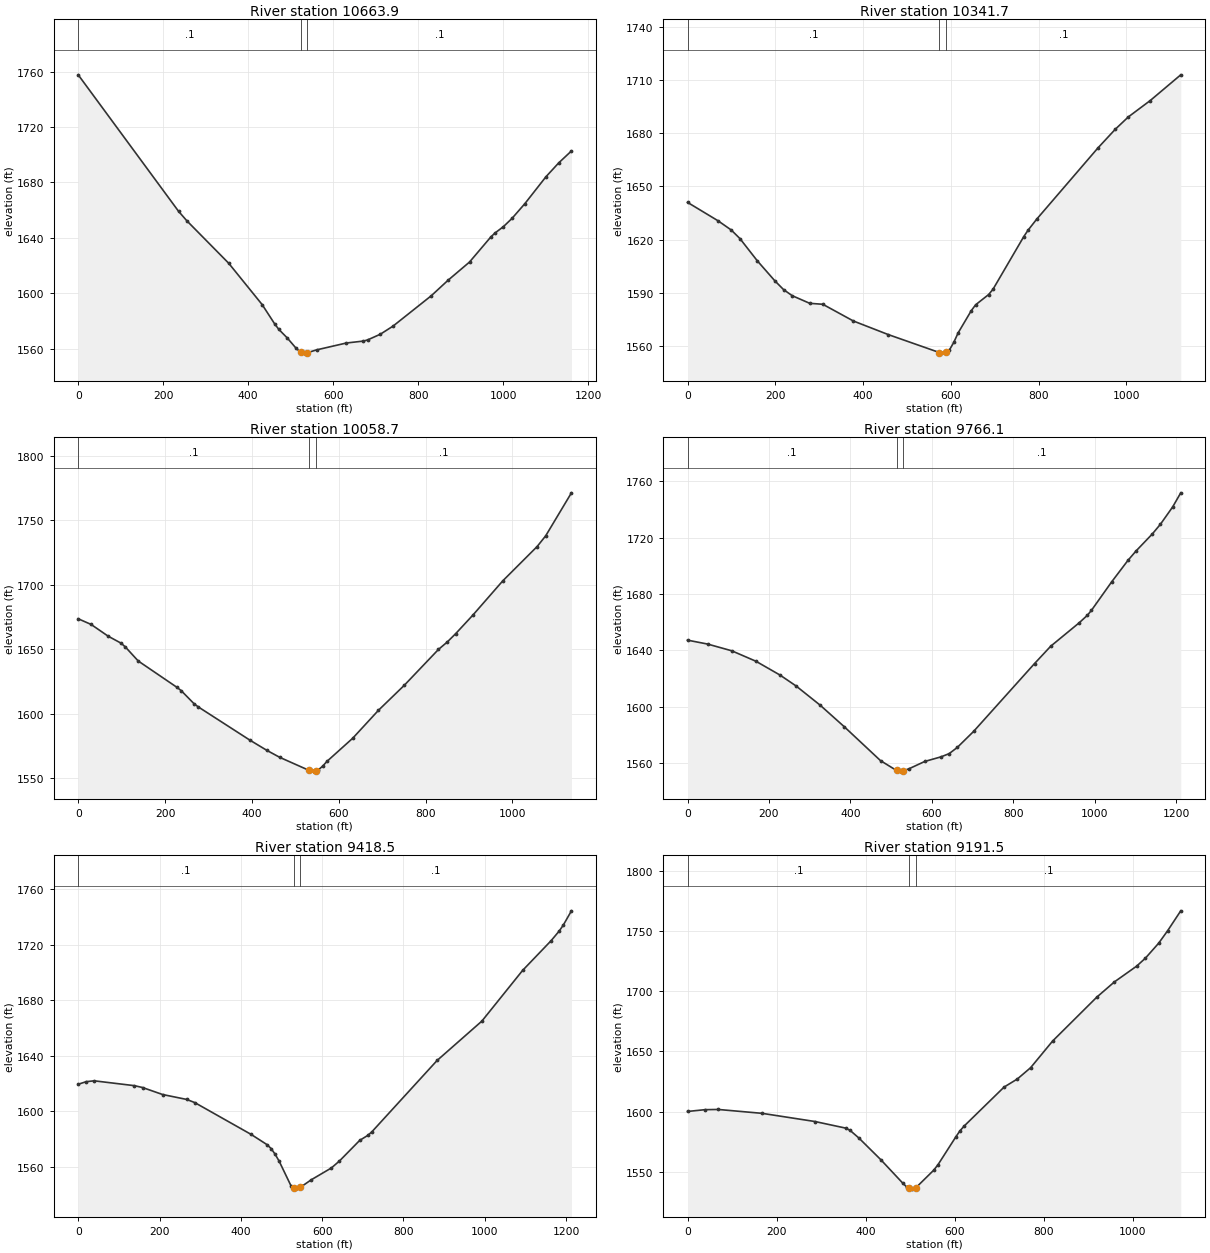
Type RM Length L Ch R = 1 ,10663.9 ,331,322.2,313.9
XS GIS Cut Line= 3
     1935947.826      355933.263     1936115.824      355429.266
     1936295.324      354825.872
#Sta/Elev= 30
       0 1757.66   236.1 1659.17   255.8 1652.25   354.2 1621.64   432.9 1591.79
   462.4 1577.85   472.2 1573.87   491.9 1567.74   511.6  1560.7   521.4 1557.86
   523.8 1557.59   531.3 1556.75   538.8 1557.01   561.2 1559.11   631.2 1564.06
   671.2 1565.45   681.2 1566.29   711.1 1570.41   741.1 1576.29     831 1598.19
     871 1609.52     921 1622.52   970.9 1640.55   980.9 1643.46  1000.9 1648.11
  1020.9    1654  1050.9 1664.55  1100.8 1684.07  1130.8 1694.07  1160.8  1702.7
#Mann= 3 , 0 , 0
       0      .1       0   523.8    .045       0   538.8      .1       0
Bank Sta=523.8,538.8
XS Rating Curve= 0 ,0
Exp/Cntr=0.3,0.1

Type RM Length L Ch R = 1 ,10341.7 ,275.5,283,290.7
XS GIS Cut Line= 2
      1936464.69      355948.608     1936375.983      354828.259
#Sta/Elev= 30
       0 1641.04    69.6 1630.66    99.5  1625.5   119.4 1620.66   159.1  1608.1
   198.9 1596.88   218.8 1591.92   238.7 1588.46   278.5 1584.18   308.3 1583.64
   377.9 1574.23   457.5 1566.57     574 1556.46   586.8 1556.13     589 1556.52
   596.7 1557.88   606.7 1562.16   616.6 1567.52   646.5 1580.01   656.4 1583.33
   686.2 1589.14   696.2 1592.14   765.8 1621.59   775.8 1625.31   795.6 1631.56
   934.9 1671.61   974.7 1682.21  1004.5 1689.17  1054.2 1698.35  1123.9 1712.87
#Mann= 3 , 0 , 0
       0      .1       0     574    .045       0     589      .1       0
Bank Sta=574,589
XS Rating Curve= 0 ,0
Exp/Cntr=0.3,0.1

Type RM Length L Ch R = 1 ,10058.7 ,299,292.4,285.9
XS GIS Cut Line= 3
     1936551.981       355953.05     1936705.295       355370.23
       1936650.9      354839.607
#Sta/Elev= 30
       0 1673.52    29.6 1669.15    69.2 1659.97    98.8 1654.59   108.7 1651.62
   138.3 1640.76   227.2  1620.4   237.1 1617.82   266.8 1607.63   276.6 1605.15
   395.2 1579.43   434.7 1571.42   464.3 1566.02   532.2 1555.85   543.4 1555.35
   547.2 1555.73   553.2 1556.34   563.1 1559.24     573 1562.93   632.3 1580.88
   691.6 1602.56   750.8 1621.85   829.8 1649.76   849.6 1655.38   869.4 1661.98
   908.9 1676.33     978 1702.99    1057 1729.56  1076.8 1737.91    1136 1771.21
#Mann= 3 , 0 , 0
       0      .1       0   532.2    .045       0   547.2      .1       0
Bank Sta=532.2,547.2
XS Rating Curve= 0 ,0
Exp/Cntr=0.3,0.1

Type RM Length L Ch R = 1 ,9766.1  ,374.7,347.5,320.2
XS GIS Cut Line= 3
     1936992.616      356002.693     1936972.772      355430.276
     1936729.986      354839.537
#Sta/Elev= 30
       0  1647.3    49.4 1644.52   108.6 1639.75   167.9 1632.34   227.1 1622.53
   266.6 1614.78   325.9  1601.1   385.1  1585.8     474 1561.76   513.4 1554.77
   523.4 1554.31   528.4 1554.51   543.1 1555.87   582.7 1561.18   622.7 1564.46
   642.6 1566.73   662.6 1571.13   702.5 1582.46   852.2 1630.65   892.1 1643.02
     962 1659.63   981.9 1664.92   991.9  1668.4  1041.8 1688.72  1081.7 1703.94
  1101.7 1710.65  1141.6 1722.71  1161.6 1729.64  1191.5 1741.87  1211.4  1751.9
#Mann= 3 , 0 , 0
       0      .1       0   513.4    .045       0   528.4      .1       0
Bank Sta=513.4,528.4
XS Rating Curve= 0 ,0
Exp/Cntr=0.3,0.1

Type RM Length L Ch R = 1 ,9418.5  ,224.5,226.8,229.3
XS GIS Cut Line= 3
     1937705.828      355496.232     1937089.225       355282.89
     1936790.304      354808.323
#Sta/Elev= 30
       0 1619.57    19.8 1621.45    39.5 1622.05   138.4 1618.56   158.2 1617.24
   207.6  1612.2   266.9 1608.66   286.7  1606.4   425.1 1583.55   464.6 1576.12
   474.5 1573.33   484.4 1569.26   494.3 1564.25     524 1546.19   531.2 1544.68
   533.8 1544.14   546.2 1545.39   573.4 1550.88   622.8 1559.38   642.6 1564.37
   692.5 1579.22   712.6 1582.84   722.6 1585.43   882.8 1636.69     993 1665.02
  1093.2 1701.48  1163.2 1722.83  1183.3 1729.84  1193.3  1734.1  1213.3 1744.34
#Mann= 3 , 0 , 0
       0      .1       0   531.2    .045       0   546.2      .1       0
Bank Sta=531.2,546.2
XS Rating Curve= 0 ,0
Exp/Cntr=0.3,0.1

Type RM Length L Ch R = 1 ,9191.5  ,308.9,327.3,345.6
XS GIS Cut Line= 3
     1937720.615      355321.101     1937167.466      355059.083
     1936799.897       354725.67
#Sta/Elev= 30
       0 1600.17    39.5 1601.67    69.1 1601.84   167.8 1598.61   286.3 1591.84
   355.4 1586.36   365.3 1584.48     385 1578.16   434.4 1560.12   483.7 1540.67
   493.6 1537.13     498  1536.5   503.5 1535.72     513 1536.85   552.8 1551.29
   562.7 1555.92   602.2 1578.69   612.1 1584.08     622 1588.22   711.3 1620.41
   741.1 1627.12   770.9 1636.49   820.5 1658.67   919.8 1695.11   959.4 1707.76
  1009.1 1720.77  1028.9 1727.42  1058.7 1739.84  1078.6 1750.07  1108.3  1766.7
#Mann= 3 , 0 , 0
       0      .1       0     498    .045       0     513      .1       0
Bank Sta=498,513
XS Rating Curve= 0 ,0
Exp/Cntr=0.3,0.1

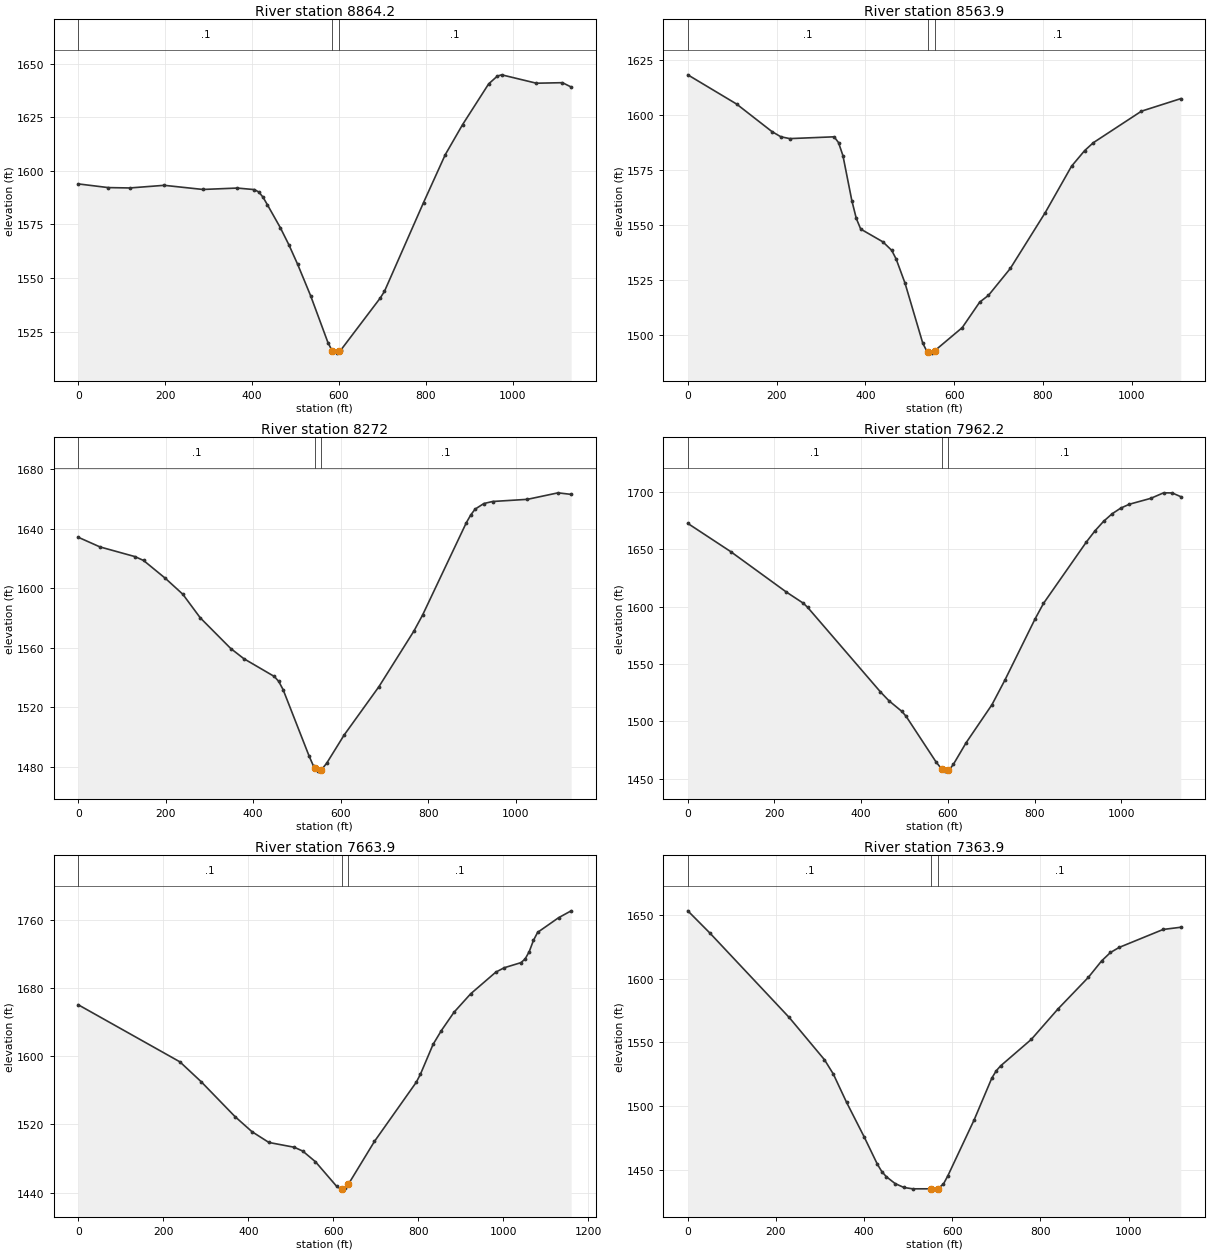
Type RM Length L Ch R = 1 ,8864.2  ,310.1,300.4,292.4
XS GIS Cut Line= 3
     1937817.739      355364.496     1937516.823      355009.955
     1937309.251      354373.561
#Sta/Elev= 30
       0  1593.9    69.3 1592.18   118.7 1592.01   197.9 1593.24   286.9 1591.31
   366.1 1591.96   405.7 1591.24   415.6 1590.12   425.4  1587.7   435.3 1584.21
     465 1573.56     485 1565.46     505 1556.44     535 1541.73   574.9 1519.87
   584.9 1515.94   594.9 1515.04   599.9 1515.82   604.9  1516.6   694.8 1540.64
   704.8 1543.83   794.7  1585.2   844.7 1607.51   884.6 1621.54   944.6 1640.52
   964.6 1644.14   974.6 1644.73  1054.5 1640.82  1114.4 1641.07  1134.4 1639.06
#Mann= 3 , 0 , 0
       0      .1       0   584.9    .045       0   599.9      .1       0
Bank Sta=584.9,599.9
XS Rating Curve= 0 ,0
Exp/Cntr=0.3,0.1

Type RM Length L Ch R = 1 ,8563.9  ,284,291.7,297.7
XS GIS Cut Line= 3
     1938113.647      355165.279     1937738.133      354764.459
     1937384.266      354328.767
#Sta/Elev= 30
       0 1618.37   109.8 1605.08   189.7  1592.5   209.7 1590.15   229.7 1589.32
   329.6 1590.14   339.5 1587.52   349.5 1581.53   369.5 1561.09   379.5 1552.99
   389.5 1548.12   439.4 1542.31   459.4 1538.42   469.4 1534.44   489.3  1523.5
   529.3 1496.15   539.3 1492.16   541.7 1492.03   549.2 1491.62   556.7 1492.79
   618.2 1503.24   657.6 1514.87   677.3 1517.93   726.5 1530.18   805.3 1555.65
   864.4 1576.74   893.9 1583.85   913.6 1587.47  1021.9 1601.81  1110.5 1607.53
#Mann= 3 , 0 , 0
       0      .1       0   541.7    .045       0   556.7      .1       0
Bank Sta=541.7,556.7
XS Rating Curve= 0 ,0
Exp/Cntr=0.3,0.1

Type RM Length L Ch R = 1 ,8272    ,322,309.5,297
XS GIS Cut Line= 3
     1938184.901      355116.255     1937898.933      354447.708
     1937649.208       354136.17
#Sta/Elev= 30
       0 1634.17    49.8 1627.66   129.5 1621.18   149.4 1618.57   199.2 1606.58
   239.1  1595.9   278.9 1580.09   348.6 1559.49   378.5 1552.67   448.2 1540.72
   458.2 1537.41   468.2 1531.92   527.9 1487.14   537.9 1480.44   540.6 1479.56
   547.8 1477.21   555.6 1478.06   567.8 1482.52   607.6 1501.39   687.3 1533.94
   767.1  1571.2     787 1581.99   886.8 1643.86   896.8 1649.02   906.8 1652.99
   926.8 1656.75   946.7 1658.14  1026.6  1659.6  1096.5 1663.96  1126.4 1662.91
#Mann= 3 , 0 , 0
       0      .1       0   540.6    .045       0   555.6      .1       0
Bank Sta=540.6,555.6
XS Rating Curve= 0 ,0
Exp/Cntr=0.3,0.1

Type RM Length L Ch R = 1 ,7962.2  ,286.3,298.4,314.4
XS GIS Cut Line= 3
     1938554.112      354827.477      1938251.93      354462.265
     1937710.256      354079.065
#Sta/Elev= 30
       0  1672.5    98.8 1647.97   227.1 1612.78   266.6 1602.96   276.5 1599.37
   444.4 1525.76   464.1    1518   493.8 1508.77   503.7 1504.46     573 1464.58
   585.6 1458.65   592.9 1456.69   600.6 1457.44   602.8 1457.65   612.7 1462.54
   642.4 1481.54   701.8 1514.55   731.5 1535.87   800.8 1588.91   820.6 1602.74
   919.7 1656.32   939.5    1666   959.3 1674.27   979.1 1680.89   998.9  1685.8
  1018.7 1689.19  1068.2 1694.32  1097.9 1699.14  1117.7 1699.06  1137.5  1695.8
#Mann= 3 , 0 , 0
       0      .1       0   585.6    .045       0   600.6      .1       0
Bank Sta=585.6,600.6
XS Rating Curve= 0 ,0
Exp/Cntr=0.3,0.1

Type RM Length L Ch R = 1 ,7663.9  ,292.6,300.3,304.2
XS GIS Cut Line= 3
     1938619.728      354778.155      1938368.58      354202.725
     1938241.236      353686.688
#Sta/Elev= 30
       0 1660.39   239.2  1593.4     289  1570.2   368.7 1529.22   408.6  1511.5
   448.5  1498.8   508.3 1493.16   528.2 1488.67   558.1 1476.15   607.9 1447.32
   617.9 1444.04   620.3 1444.29   627.8 1445.06   635.3 1449.63   696.8 1500.03
   795.2  1569.5     805 1578.94   834.6 1613.82   854.2  1630.1   883.8 1651.52
   923.1 1673.23   982.2 1698.64  1001.9 1703.78  1041.2 1709.76  1051.1 1714.06
  1060.9 1722.79  1070.8 1735.97  1080.6 1745.33  1129.8 1762.48  1159.4 1770.58
#Mann= 3 , 0 , 0
       0      .1       0   620.3    .045       0   635.3      .1       0
Bank Sta=620.3,635.3
XS Rating Curve= 0 ,0
Exp/Cntr=0.3,0.1

Type RM Length L Ch R = 1 ,7363.9  ,294.2,296.8,299.4
XS GIS Cut Line= 3
     1938703.101       354766.71     1938665.694      354207.776
     1938629.758      353650.645
#Sta/Elev= 30
       0 1653.15      50 1635.75   230.1 1569.45   310.1  1536.3   330.1 1525.12
   360.1 1502.96   400.1  1475.8   430.1 1454.31   440.1  1448.6   450.2  1444.6
   470.2 1439.18   490.2 1436.07   510.2 1435.01   552.7 1435.02   560.2 1434.77
   567.7  1435.2   580.1 1438.84   590.1 1445.29   649.9 1489.29   689.8 1521.93
   699.8 1527.62   709.7 1531.48   779.5 1552.31   839.3 1575.92   909.1 1601.06
     939 1613.89     959 1620.46   978.9 1624.46  1078.6 1638.54  1118.5 1640.26
#Mann= 3 , 0 , 0
       0      .1       0   552.7    .045       0   567.7      .1       0
Bank Sta=552.7,567.7
XS Rating Curve= 0 ,0
Exp/Cntr=0.3,0.1

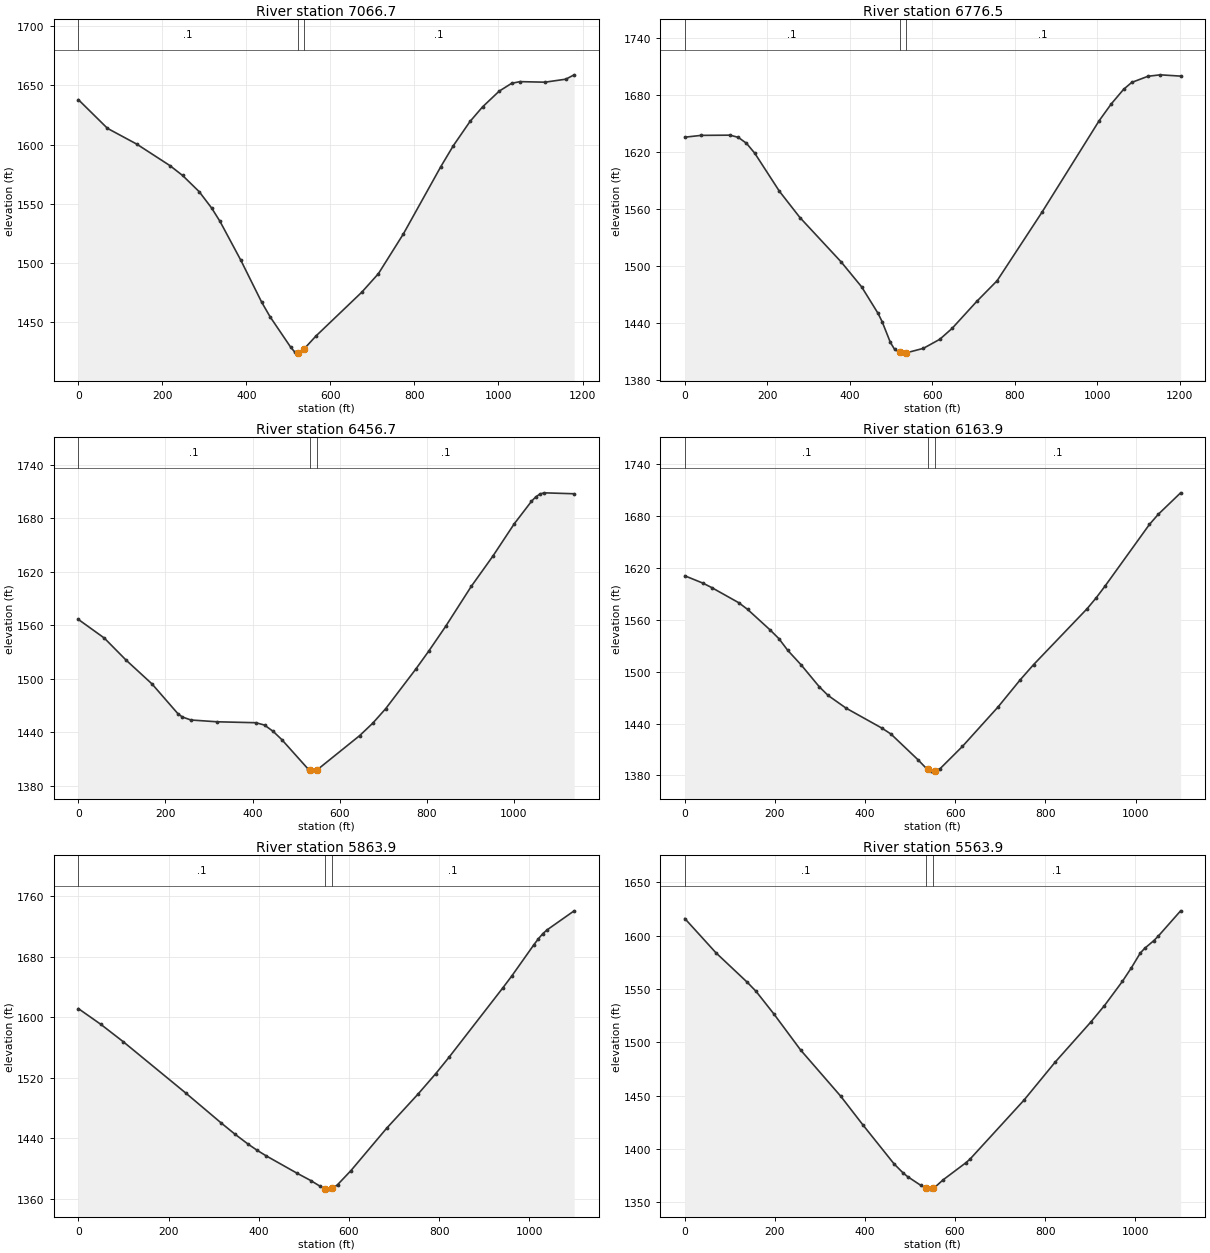
Type RM Length L Ch R = 1 ,7066.7  ,317.6,290.1,262.5
XS GIS Cut Line= 3
      1938936.49      354760.822     1938965.201      354136.562
     1938712.528      353642.258
#Sta/Elev= 30
       0 1637.98    69.4 1613.67   138.9 1600.38   218.2 1582.13     248 1573.87
   287.7 1560.12   317.4 1546.23   337.3 1534.94   386.9 1502.04   436.4 1466.66
   456.3  1454.4   505.9 1428.37   515.8 1424.28   521.7 1423.87   525.7  1423.6
   536.7 1426.91   565.4 1438.02   674.5 1475.08   714.1 1490.74   773.6  1524.4
   862.8 1581.35   892.6 1599.06   932.2 1619.49     962  1631.8  1001.6 1645.12
  1031.4 1651.77  1051.2 1653.18  1110.7 1652.72  1160.2 1655.25  1180.1 1658.94
#Mann= 3 , 0 , 0
       0      .1       0   521.7    .045       0   536.7      .1       0
Bank Sta=521.7,536.7
XS Rating Curve= 0 ,0
Exp/Cntr=0.3,0.1

Type RM Length L Ch R = 1 ,6776.5  ,323.3,319.9,316.4
XS GIS Cut Line= 3
     1939680.301      354312.629     1939056.179      354047.403
     1938778.079      353602.927
#Sta/Elev= 30
       0    1636    39.9 1637.92   109.7 1638.14   129.6 1635.85   149.6 1629.57
   169.5 1619.23   229.4 1579.11   279.2  1551.4     379 1504.78   428.8 1478.47
   468.7 1450.51   478.7 1441.63   498.6 1419.89   508.6  1412.8   520.7 1409.49
   528.6 1408.68   535.7 1408.81   578.4 1413.69   618.3 1423.23   648.2 1434.71
   707.8 1463.04   757.3 1484.88   866.1 1556.95  1004.6  1653.2  1034.3 1671.11
    1064 1686.32  1083.7 1693.64  1123.3 1700.14    1153 1701.65  1202.4  1700.3
#Mann= 3 , 0 , 0
       0      .1       0   520.7    .045       0   535.7      .1       0
Bank Sta=520.7,535.7
XS Rating Curve= 0 ,0
Exp/Cntr=0.3,0.1

Type RM Length L Ch R = 1 ,6456.7  ,287.6,292.7,298.9
XS GIS Cut Line= 3
     1939860.855      353955.857     1939185.369      353789.024
     1938823.833      353533.845
#Sta/Elev= 30
       0 1566.54    59.6  1545.6   109.3 1520.99     169 1494.18   228.6  1460.7
   238.6 1457.04   258.4 1453.63   318.1 1451.62   407.5 1450.56   427.4 1447.93
   447.3 1440.84   467.2 1431.57   526.8    1399   531.8 1397.61   536.8 1396.22
   546.8 1397.08   646.1 1436.18   675.9 1450.03   705.6 1466.32   774.4 1510.54
     804 1530.63   843.3 1558.75   902.3 1603.78   951.5 1637.45  1000.6 1673.74
    1040 1698.91  1049.8 1703.91  1059.6 1707.25  1069.5 1708.63  1138.3 1707.58
#Mann= 3 , 0 , 0
       0      .1       0   531.8    .045       0   546.8      .1       0
Bank Sta=531.8,546.8
XS Rating Curve= 0 ,0
Exp/Cntr=0.3,0.1

Type RM Length L Ch R = 1 ,6163.9  ,291.4,299.9,309.9
XS GIS Cut Line= 3
     1939929.141      353813.468     1939438.784      353571.902
     1938955.354      353303.012
#Sta/Elev= 30
       0 1611.01    39.8  1602.6    59.6 1597.41   119.3 1579.96   139.1 1572.23
   188.8 1548.58   208.7 1538.32   228.6 1524.62   258.4 1507.75   298.2 1482.68
     318 1472.53   357.8 1457.87   437.3 1434.76   457.2 1427.97   516.8 1398.41
   536.7 1387.71   539.1 1387.06   546.6 1385.02   554.1 1385.12   566.4 1387.94
   615.8  1413.6   694.8 1459.24   744.2 1490.79   773.8 1508.33   892.4 1572.95
   912.1 1585.26   931.9 1598.92  1030.7 1670.48  1050.4 1682.25  1099.8    1707
#Mann= 3 , 0 , 0
       0      .1       0   539.1    .045       0   554.1      .1       0
Bank Sta=539.1,554.1
XS Rating Curve= 0 ,0
Exp/Cntr=0.3,0.1

Type RM Length L Ch R = 1 ,5863.9  ,298.4,299.9,295.4
XS GIS Cut Line= 3
     1939981.982      353743.437     1939608.385      353333.066
     1939293.797       352888.92
#Sta/Elev= 30
       0 1611.46    49.6 1590.71    99.1 1567.84   237.8 1499.86   317.1 1459.88
   346.8 1445.45   376.6 1431.98   396.4 1423.92   416.2 1416.65   485.6 1393.34
   515.3 1383.89   535.1 1376.63     545  1373.4   547.5 1373.18     555 1372.52
   562.5 1373.53   564.8 1373.84   574.8 1378.46   604.4 1397.07   683.6 1453.17
   752.9 1498.18   792.5 1525.44   822.2 1547.34   940.9 1638.73   960.7 1654.41
  1010.2 1696.18  1020.1 1703.98    1030 1710.78  1039.9 1715.91  1099.2 1740.82
#Mann= 3 , 0 , 0
       0      .1       0   547.5    .045       0   562.5      .1       0
Bank Sta=547.5,562.5
XS Rating Curve= 0 ,0
Exp/Cntr=0.3,0.1

Type RM Length L Ch R = 1 ,5563.9  ,314.3,299.9,291.6
XS GIS Cut Line= 3
     1940191.118       353585.24     1939852.622      353159.343
     1939446.642      352778.019
#Sta/Elev= 30
       0 1616.18    69.2 1584.04   138.5 1556.51   158.3  1547.9   197.8 1526.73
   257.2 1492.92   346.2 1449.63   395.7  1422.6   464.9 1386.07   484.7 1377.72
   494.6 1374.28   524.2 1366.01   536.5 1363.31     544 1362.51   551.5  1363.5
     554 1363.83   573.9 1371.31   623.6 1387.05   633.5 1390.71   752.9  1445.8
   822.5 1481.62   902.1  1519.4   931.9 1534.58   971.7 1557.26   991.6 1569.97
  1011.5 1583.87  1021.4 1588.32  1041.3 1595.38  1051.3 1599.64    1101 1623.39
#Mann= 3 , 0 , 0
       0      .1       0   536.5    .045       0   551.5      .1       0
Bank Sta=536.5,551.5
XS Rating Curve= 0 ,0
Exp/Cntr=0.3,0.1

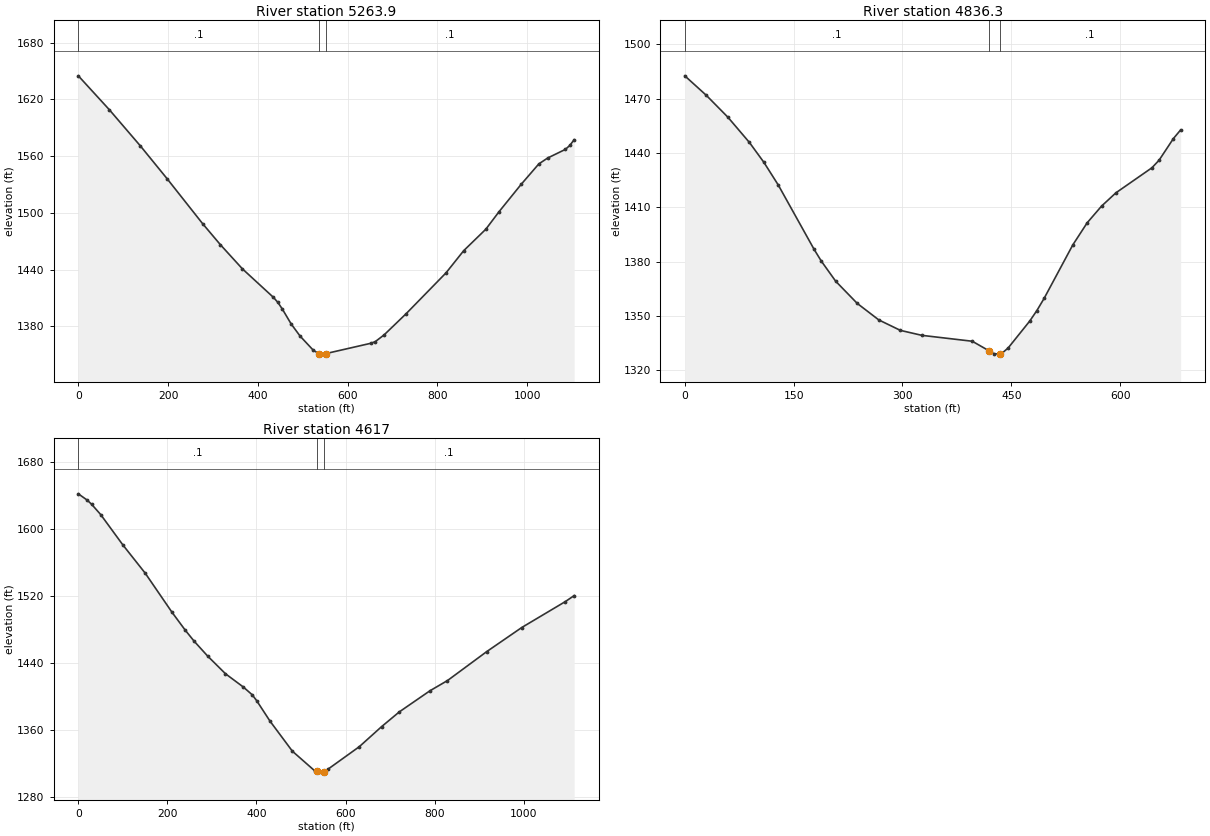
Type RM Length L Ch R = 1 ,5263.9  ,407.5,427.5,444.8
XS GIS Cut Line= 3
     1940538.396      353058.321     1940013.883      352916.563
     1939493.964      352705.512
#Sta/Elev= 30
       0 1644.93    69.2 1609.01   138.3 1570.77   197.6 1536.22   276.6 1488.77
   316.1 1466.55   365.5 1440.82   434.7 1410.63   444.5 1405.32   454.4 1398.32
   474.2 1382.48   493.9 1369.77   523.6 1354.66   535.8 1351.24   543.3 1350.68
   550.8 1351.19   651.6 1362.16   661.5 1363.92   681.2 1371.07   730.4 1393.54
     819 1436.61   858.4 1460.08   907.6 1482.73   937.1 1501.28   986.3 1530.16
  1025.7  1551.8  1045.4 1558.03  1084.8 1567.15  1094.6 1571.29  1104.4 1577.37
#Mann= 3 , 0 , 0
       0      .1       0   535.8    .045       0   550.8      .1       0
Bank Sta=535.8,550.8
XS Rating Curve= 0 ,0
Exp/Cntr=0.3,0.1

Type RM Length L Ch R = 1 ,4836.3  ,230,218.8,207.7
XS GIS Cut Line= 2
     1940286.209      352913.811     1940007.814      352289.698
#Sta/Elev= 30
       0 1482.53    29.7 1471.76    59.4  1459.7    89.1 1445.75     109 1434.81
   128.8 1422.31   178.3 1386.73   188.2 1380.28     208 1369.19   237.7 1356.96
   267.4 1347.85   297.1 1342.09   326.8 1339.34   396.2 1336.09   419.1 1330.87
   425.9 1329.22   434.1 1329.02   435.8 1328.98   445.7 1332.39   475.4 1347.21
   485.3 1353.04   495.2  1359.7   534.8 1389.25   554.6 1401.44   574.4 1410.65
   594.2 1417.98   643.8 1431.78   653.7 1435.97   673.5 1447.95   683.4 1452.68
#Mann= 3 , 0 , 0
       0      .1       0   419.1    .045       0   434.1      .1       0
Bank Sta=419.1,434.1
XS Rating Curve= 0 ,0
Exp/Cntr=0.3,0.1

Type RM Length L Ch R = 1 ,4617    ,251.4,253.1,251.6
XS GIS Cut Line= 3
     1940721.784      352776.743      1940153.38      352333.368
     1939934.873      352007.577
#Sta/Elev= 30
       0 1642.06      20  1634.5      30 1629.47    50.1 1617.34   100.1 1580.93
   150.2 1547.24   210.3 1500.56   240.3 1478.98   260.3 1465.83   290.4  1448.2
   330.4  1427.1   370.4 1411.26   390.5 1401.94   400.5 1394.86   430.5 1370.39
   480.6 1334.58   530.6 1311.21   535.6  1310.4   540.7 1309.58   550.6 1310.24
   560.7 1313.18   630.8 1339.97   680.8 1363.89   720.9 1381.65   789.5 1406.79
   828.8 1418.97     917  1453.6   995.5 1482.33  1093.6 1513.39  1113.2 1520.48
#Mann= 3 , 0 , 0
       0      .1       0   535.6    .045       0   550.6      .1       0
Bank Sta=535.6,550.6
XS Rating Curve= 0 ,0
Exp/Cntr=0.3,0.1