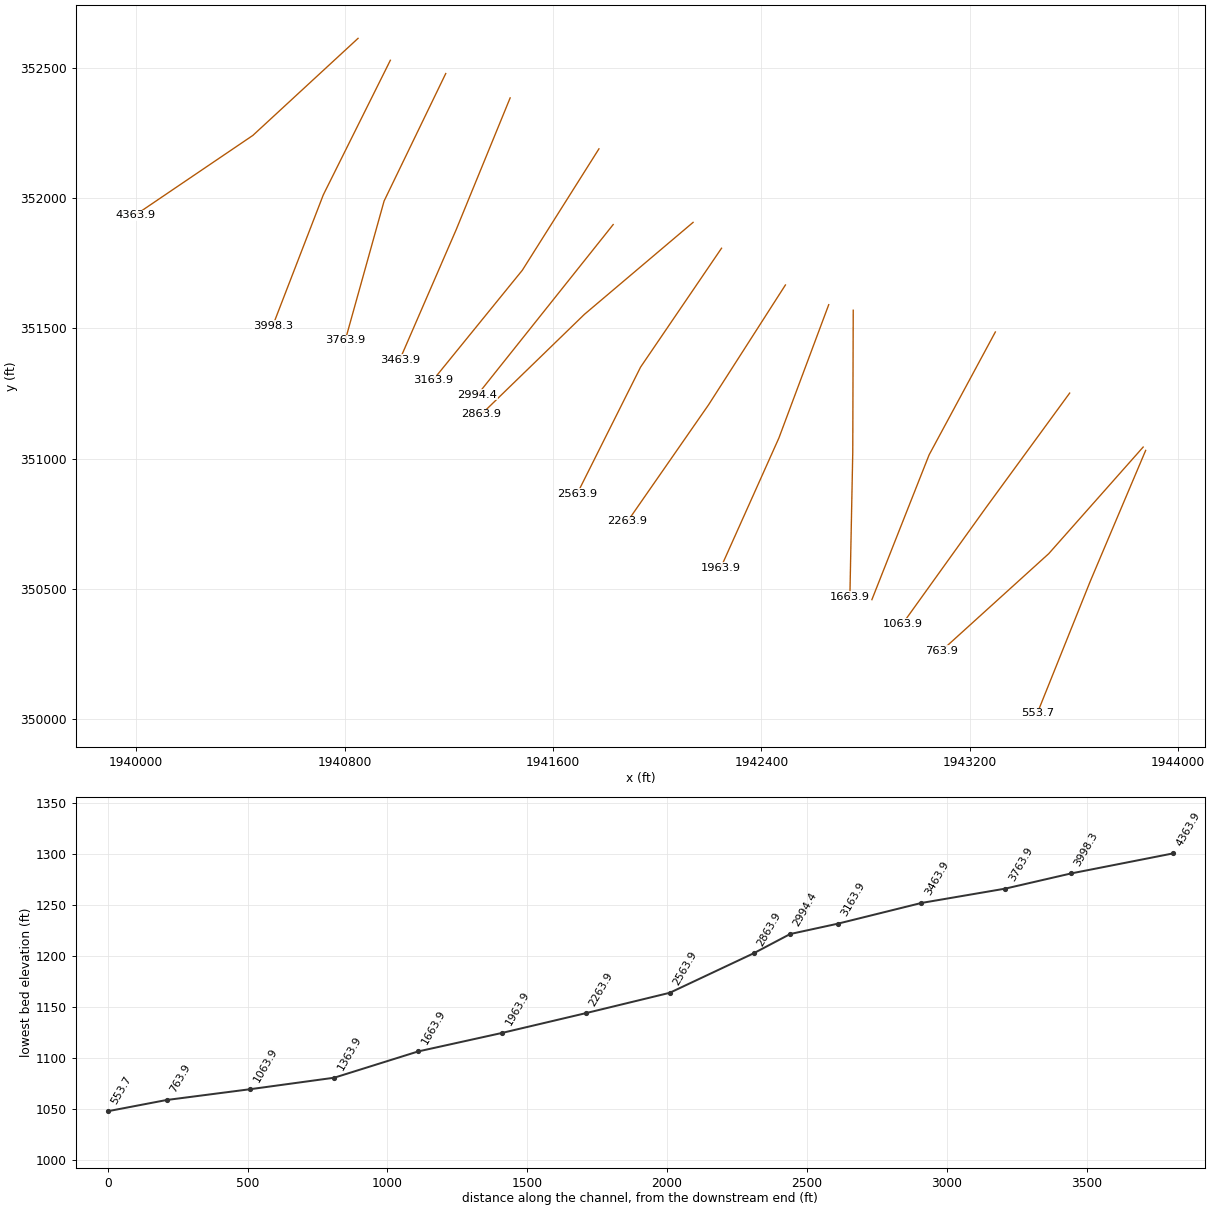
HEC-RAS study ArbckleCrk.prj: ArbckleCrk

--- ArbckleCrk.g01 (geometry) --- (continued)

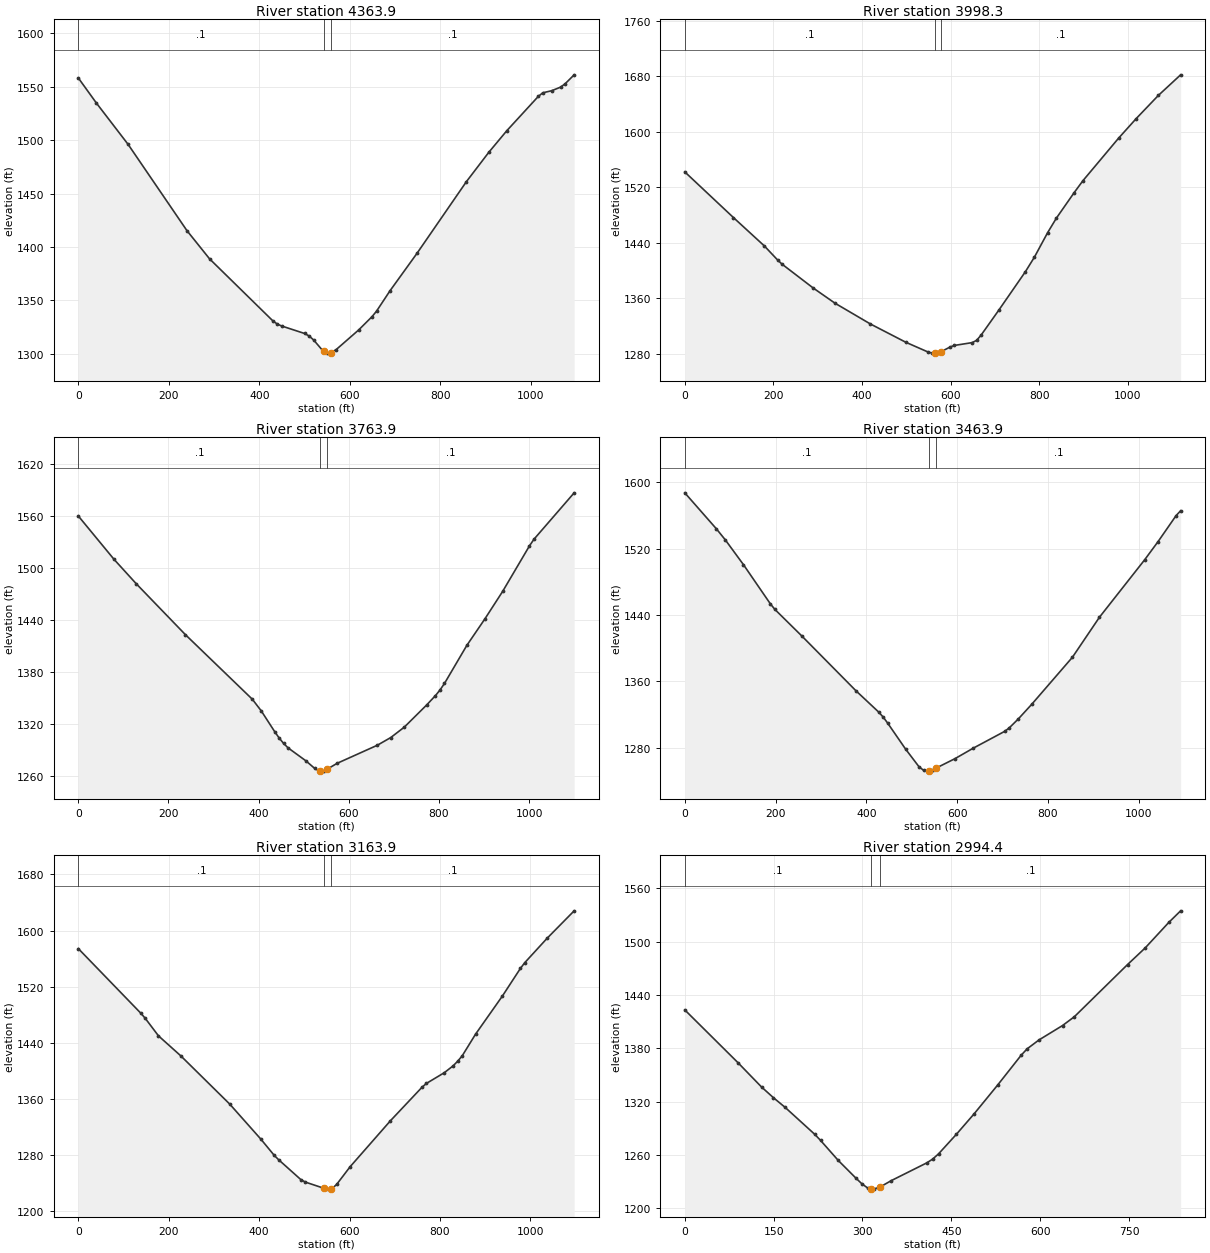
Type RM Length L Ch R = 1 ,4363.9  ,357.1,365.5,378.5
XS GIS Cut Line= 3
     1940851.573      352615.667     1940447.611      352242.295
     1939995.887      351935.692
#Sta/Elev= 30
       0 1558.26      40 1534.74     110 1496.11     240  1415.4     290 1388.98
   430.1 1330.84   440.1 1327.79   450.1 1325.99   500.1 1319.07   510.1 1316.75
   520.1    1313   540.1  1303.1   542.6  1302.5   550.1 1300.68   557.6 1300.97
   569.9 1303.97   619.6 1322.35   649.4 1334.91   659.3 1340.05     689 1359.09
   748.6  1394.1   857.8  1461.2   907.4 1488.72   947.1 1508.88  1016.6 1540.94
  1026.6 1544.37  1046.4 1546.33  1066.2 1549.73  1076.2  1552.9    1096  1561.2
#Mann= 3 , 0 , 0
       0      .1       0   542.6    .045       0   557.6      .1       0
Bank Sta=542.6,557.6
XS Rating Curve= 0 ,0
Exp/Cntr=0.3,0.1

Type RM Length L Ch R = 1 ,3998.3  ,234.2,234.6,237.5
XS GIS Cut Line= 3
     1940975.531      352531.325     1940718.017      352013.509
     1940523.635      351509.295
#Sta/Elev= 30
       0 1542.12   109.7 1476.34   179.5 1435.44   209.4  1415.2   219.4 1409.19
   289.2 1375.07     339 1352.88   418.8 1322.99   498.6 1296.68   548.4 1282.72
   558.4    1281   563.4 1281.03   568.3 1281.05   578.4 1283.15   598.3 1289.72
   608.3  1292.1   648.4 1296.14   658.4 1299.43   668.4 1306.85   708.4 1342.86
   768.4 1398.27   788.5 1418.95   818.5 1454.42   838.5 1475.61   878.5 1512.26
   898.5 1529.62   978.6  1590.6  1018.6 1619.02  1068.7 1652.45  1118.7 1681.97
#Mann= 3 , 0 , 0
       0      .1       0   563.4    .045       0   578.4      .1       0
Bank Sta=563.4,578.4
XS Rating Curve= 0 ,0
Exp/Cntr=0.3,0.1

Type RM Length L Ch R = 1 ,3763.9  ,298.5,299.7,296.6
XS GIS Cut Line= 3
     1941188.119      352480.259     1940951.483      351990.084
     1940802.442      351454.845
#Sta/Elev= 30
       0 1559.73    79.2 1509.86   128.6 1481.73   237.5 1423.21     386 1348.88
   405.8 1335.47   435.4 1311.74   445.3  1304.4   455.2 1298.15   465.1 1292.99
   504.7 1278.06   524.5 1269.21   534.4 1266.16   536.8 1266.22   544.3 1266.41
   551.8 1268.34   574.1 1275.15   663.4 1295.99   693.1 1304.82   722.9 1316.69
   772.5 1342.18   792.3 1353.12   802.3 1359.52   812.2 1367.03   861.8 1410.85
   901.5 1441.06   941.2 1472.92  1000.7 1525.32  1010.6 1532.93  1099.9 1586.42
#Mann= 3 , 0 , 0
       0      .1       0   536.8    .045       0   551.8      .1       0
Bank Sta=536.8,551.8
XS Rating Curve= 0 ,0
Exp/Cntr=0.3,0.1

Type RM Length L Ch R = 1 ,3463.9  ,303.8,300,293.8
XS GIS Cut Line= 3
     1941435.382      352386.622     1941228.772      351881.213
     1941011.611      351379.805
#Sta/Elev= 30
       0 1587.01    69.5 1543.76    89.4  1530.3   129.1 1500.68   188.6 1453.35
   198.6 1446.65   258.1 1414.59   377.2 1348.76   426.9 1323.34   436.8 1317.33
   446.7 1310.11   486.4 1278.67   516.2 1257.22   526.2 1253.09   536.1 1252.12
   538.5 1252.45     546 1253.47   553.5 1255.71   595.7 1267.26   635.4 1279.72
     705 1300.05   714.9 1304.21   734.8  1314.9   764.6 1332.68     854 1389.14
   913.6 1437.35    1013 1506.32  1042.8  1528.4  1082.5 1559.66  1092.4 1565.44
#Mann= 3 , 0 , 0
       0      .1       0   538.5    .045       0   553.5      .1       0
Bank Sta=538.5,553.5
XS Rating Curve= 0 ,0
Exp/Cntr=0.3,0.1

Type RM Length L Ch R = 1 ,3163.9  ,172,169.5,169.7
XS GIS Cut Line= 3
      1941776.23      352190.689     1941482.158      351723.989
     1941138.749      351300.662
#Sta/Elev= 30
       0 1574.26   137.9 1482.49   147.8 1475.17   177.3 1450.01   226.6 1421.57
   334.9 1352.83   403.9  1302.8   433.4 1279.76   443.3 1273.45   492.5 1245.12
   502.4  1241.7   544.1 1232.76   551.6 1231.74   559.1 1232.47   561.5 1232.71
   571.4 1238.47   601.2 1263.67   690.4 1329.17   759.8 1376.58   769.7 1382.21
   809.3 1397.49   829.1 1407.38     839 1413.89     849 1421.51   878.7 1452.54
   938.2 1506.95   977.8 1546.07   987.7 1554.44  1037.3 1589.29  1096.7 1628.09
#Mann= 3 , 0 , 0
       0      .1       0   544.1    .045       0   559.1      .1       0
Bank Sta=544.1,559.1
XS Rating Curve= 0 ,0
Exp/Cntr=0.3,0.1

Type RM Length L Ch R = 1 ,2994.4  ,135.1,130.8,127.9
XS GIS Cut Line= 2
     1941830.872      351899.552     1941309.565      351244.507
#Sta/Elev= 30
       0 1423.13    89.7 1363.86   129.6 1336.45   149.5 1324.53   169.4 1313.57
   219.3 1283.34   229.2 1276.46   259.1 1253.92     289 1233.97     299 1227.65
     309 1222.81   314.9 1222.12   318.9 1221.65   329.9 1224.13   348.8 1231.27
   408.6 1251.17   418.6 1255.45   428.6  1261.4   458.4 1283.17   488.4  1306.2
   528.2 1338.62   568.1  1372.3     578 1379.35     598 1389.35   637.8 1405.55
   657.8 1415.48   747.5 1474.06   777.4 1492.82   817.2 1521.47   837.2 1534.52
#Mann= 3 , 0 , 0
       0      .1       0   314.9    .045       0   329.9      .1       0
Bank Sta=314.9,329.9
XS Rating Curve= 0 ,0
Exp/Cntr=0.3,0.1

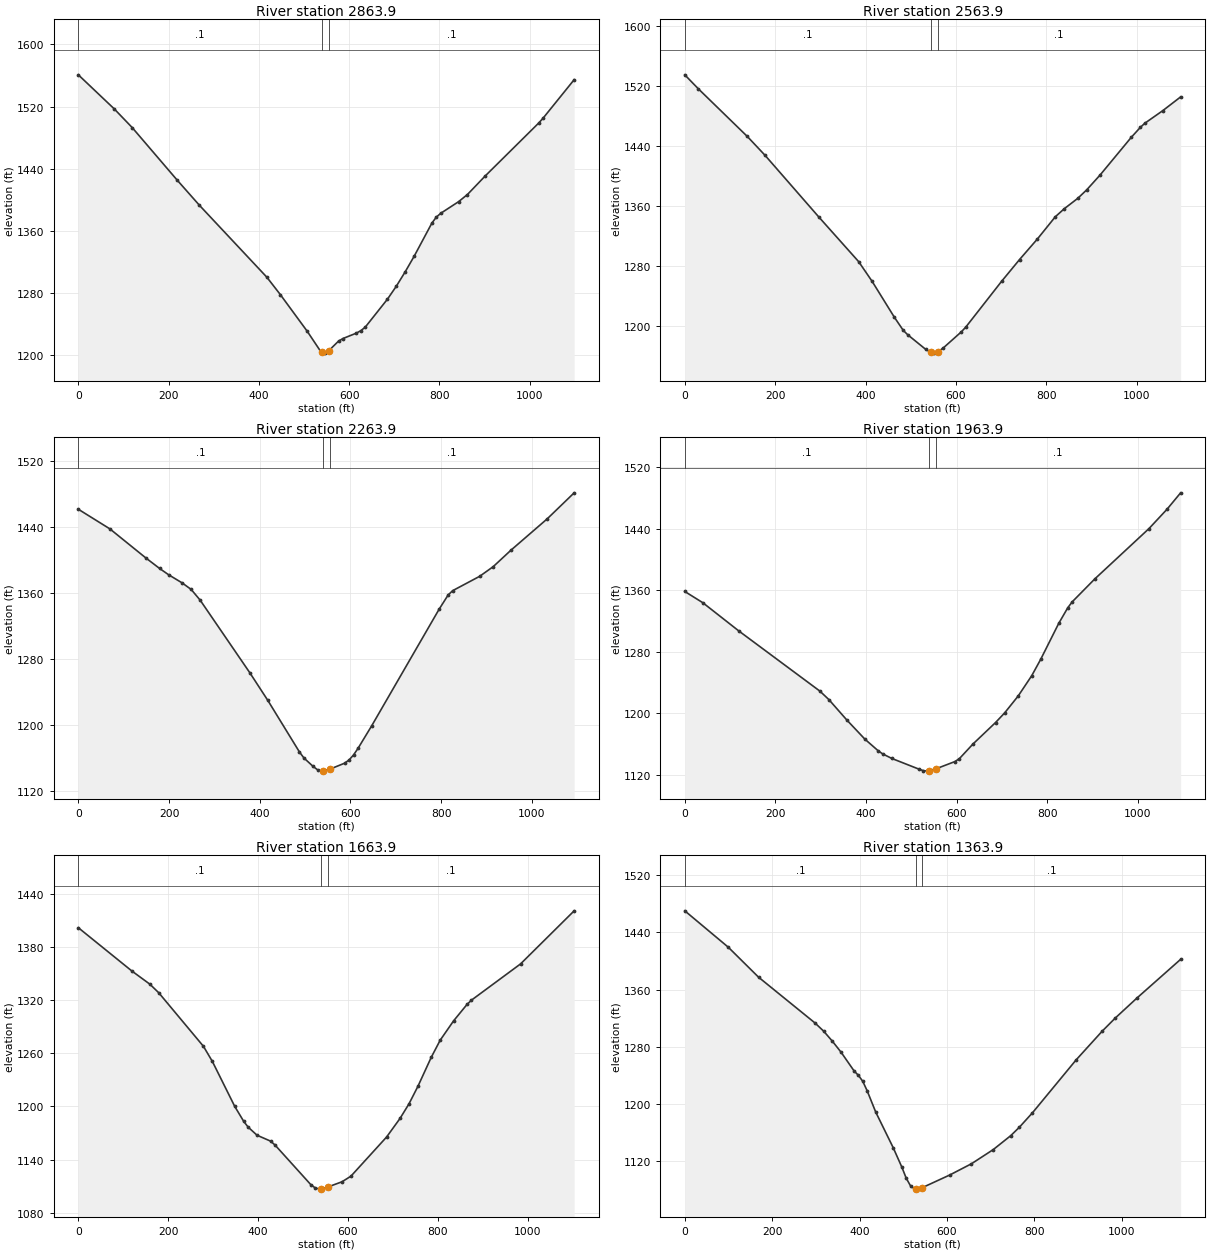
Type RM Length L Ch R = 1 ,2863.9  ,293.7,299.7,307.2
XS GIS Cut Line= 3
     1942137.555      351907.945     1941720.464      351554.336
     1941324.898        351169.9
#Sta/Elev= 30
       0  1560.9    79.5 1517.09   119.3 1493.03   218.7 1425.57   268.4  1392.9
   417.6 1300.46   447.4 1278.14     507 1230.92   536.9 1204.87   539.3 1204.35
   546.8 1202.74   554.3 1205.57   576.4 1218.18   586.2 1221.53   615.8 1228.44
   625.6 1231.57   635.5 1236.08   684.7 1272.11   704.4 1288.82   724.1 1307.39
   743.8 1327.26   783.2 1370.06   793.1  1377.8   802.9 1382.72   842.3 1397.62
     862 1406.88   901.4 1430.77  1019.6 1498.71  1029.5 1505.07  1098.4 1554.66
#Mann= 3 , 0 , 0
       0      .1       0   539.3    .045       0   554.3      .1       0
Bank Sta=539.3,554.3
XS Rating Curve= 0 ,0
Exp/Cntr=0.3,0.1

Type RM Length L Ch R = 1 ,2563.9  ,299.3,300,296.8
XS GIS Cut Line= 3
     1942246.798      351808.557     1941936.129      351351.545
     1941692.471      350864.232
#Sta/Elev= 30
       0 1534.77    29.6 1516.36   138.2 1452.78   177.6 1427.57     296 1345.83
   384.8 1285.94   414.5 1259.78   463.8  1211.9   483.5 1194.42   493.4 1188.54
   532.9 1169.24   545.1 1165.05   552.6 1164.08   560.1 1165.68   572.4 1171.16
     612 1192.39     622 1198.82   701.2 1259.74   740.8 1288.66   780.4  1316.1
   820.1 1345.74   839.9 1356.43   869.6 1370.18   889.4 1381.47   919.1 1401.28
   988.5 1451.75  1008.3 1464.79  1018.2  1470.3  1057.8 1487.01  1097.4 1505.35
#Mann= 3 , 0 , 0
       0      .1       0   545.1    .045       0   560.1      .1       0
Bank Sta=545.1,560.1
XS Rating Curve= 0 ,0
Exp/Cntr=0.3,0.1

Type RM Length L Ch R = 1 ,2263.9  ,295.1,299.9,304.1
XS GIS Cut Line= 3
     1942492.069      351667.314     1942196.997      351206.431
     1941885.774      350757.836
#Sta/Elev= 30
       0 1462.03    69.6 1438.19   149.2 1402.77   179.1 1390.19     199 1382.54
   228.8 1372.66   248.8 1364.68   268.6 1351.69   378.1 1263.55   417.9 1229.89
   487.6  1167.3   497.5 1160.04   517.4 1149.95   527.4 1145.78   537.3 1144.13
   539.7 1144.35   554.7 1146.54     587 1153.74   596.9 1157.66   606.8 1163.76
   616.7 1171.81   646.5 1198.85   795.4 1340.63   815.3 1357.91   825.2 1363.16
   884.8 1380.61   914.6 1392.29   954.2 1412.51  1033.7 1450.35  1093.2 1481.97
#Mann= 3 , 0 , 0
       0      .1       0   539.7    .045       0   554.7      .1       0
Bank Sta=539.7,554.7
XS Rating Curve= 0 ,0
Exp/Cntr=0.3,0.1

Type RM Length L Ch R = 1 ,1963.9  ,292,300,309.2
XS GIS Cut Line= 3
     1942658.328      351591.492     1942467.285      351079.422
     1942243.527      350579.166
#Sta/Elev= 30
       0 1358.22    39.8 1343.61   119.2 1306.95   298.1 1228.79     318 1217.76
   357.7 1191.18   397.5 1166.32   427.3 1150.99   437.2 1147.02   457.1 1141.19
   516.7 1127.36   526.7 1125.32   536.6 1124.73     539 1125.01     554 1127.61
   596.4 1137.18   606.3 1141.02   636.2 1159.99     686 1187.88     706 1200.33
   735.9 1222.31   765.8 1248.67   785.7 1270.04   825.5 1316.75   845.5 1337.09
   855.4 1344.84   905.2 1374.59  1024.8    1440  1064.7 1465.18  1094.6 1486.45
#Mann= 3 , 0 , 0
       0      .1       0     539    .045       0     554      .1       0
Bank Sta=539,554
XS Rating Curve= 0 ,0
Exp/Cntr=0.3,0.1

Type RM Length L Ch R = 1 ,1663.9  ,310.9,299.8,291.7
XS GIS Cut Line= 3
     1942752.388      351570.106     1942750.583       351023.35
     1942739.481      350467.269
#Sta/Elev= 30
       0 1401.92   119.3 1352.93   159.1 1338.14   178.9 1328.43   278.4 1267.87
   298.2 1250.81   347.9 1200.08   367.8 1183.23   377.8  1176.6   397.6 1167.47
   427.5 1160.84   437.4  1156.5   516.9 1111.79   526.9 1107.94   536.8 1106.58
   539.3 1106.79   554.3 1108.86   586.5 1114.86   606.4  1121.2   685.8 1165.49
   715.6 1186.42   735.5 1202.87   755.3 1222.58   785.1 1255.52     805 1274.87
   834.8  1296.7   864.6 1315.21   874.5 1320.06   983.8 1361.04    1103    1421
#Mann= 3 , 0 , 0
       0      .1       0   539.3    .045       0   554.3      .1       0
Bank Sta=539.3,554.3
XS Rating Curve= 0 ,0
Exp/Cntr=0.3,0.1

Type RM Length L Ch R = 1 ,1363.9  ,302.9,299.8,294.3
XS GIS Cut Line= 3
     1943297.876      351486.491     1943043.622      351013.945
     1942824.016      350457.231
#Sta/Elev= 30
       0 1470.24    99.4 1419.41   168.9 1377.38   298.1 1313.32     318 1301.81
   337.9 1287.78   357.7 1272.49   387.6 1246.18   397.5 1240.03   407.4  1231.7
   417.4 1218.58   437.2 1188.52     477 1138.96   496.9 1111.64   506.8 1096.31
   516.7 1085.46   526.7 1080.86   529.1 1080.96   544.1 1083.06   606.4 1100.58
   656.3 1116.38   706.2 1136.21   746.1 1155.63     766 1167.49   795.9 1187.64
   895.7 1261.56   955.5 1301.82   985.4 1320.18  1035.3 1348.34  1135.1 1402.36
#Mann= 3 , 0 , 0
       0      .1       0   529.1    .045       0   544.1      .1       0
Bank Sta=529.1,544.1
XS Rating Curve= 0 ,0
Exp/Cntr=0.3,0.1

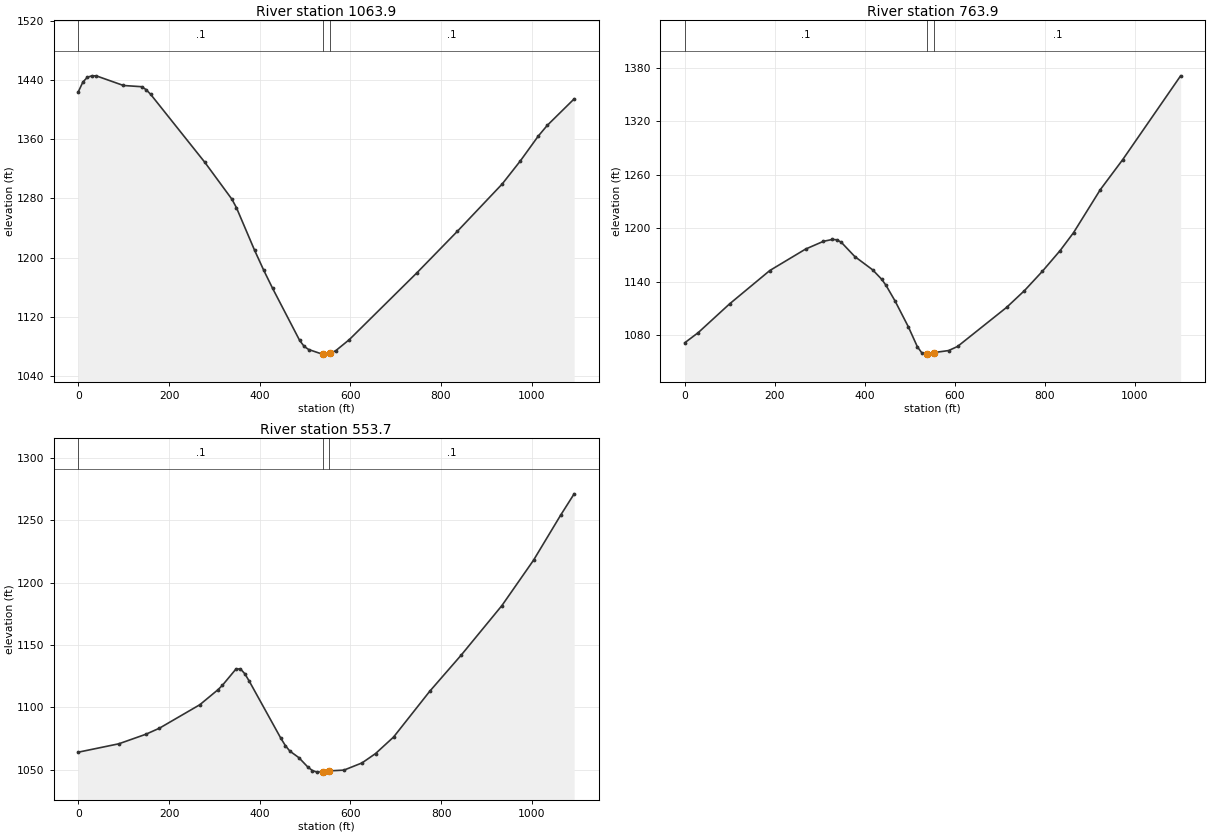
Type RM Length L Ch R = 1 ,1063.9  ,302.1,300,295.2
XS GIS Cut Line= 3
     1943583.139      351251.507     1943260.224      350808.762
     1942942.421      350365.269
#Sta/Elev= 30
       0 1424.06      10  1437.1    19.9 1443.59    29.9 1445.55    39.8 1445.46
    99.6 1432.49   139.5 1430.86   149.4 1426.96   159.4 1420.62     279 1328.71
   338.8 1278.82   348.7 1267.49   388.6 1210.12   408.5 1183.46   428.4 1158.59
   488.2 1088.06   498.2    1080   508.1 1075.84     538 1069.62   540.5 1069.62
   555.5 1070.85   567.8 1074.29   597.6 1089.18   746.4 1179.25   835.7 1235.35
   934.9 1299.46   974.6 1330.38  1014.2 1363.95  1034.1 1378.52  1093.6  1414.4
#Mann= 3 , 0 , 0
       0      .1       0   540.5    .045       0   555.5      .1       0
Bank Sta=540.5,555.5
XS Rating Curve= 0 ,0
Exp/Cntr=0.3,0.1

Type RM Length L Ch R = 1 ,763.9   ,202.7,210.1,220.5
XS GIS Cut Line= 3
     1943865.295      351043.987     1943503.018      350634.223
     1943091.734      350260.788
#Sta/Elev= 30
       0 1071.75    29.8 1083.08    99.4 1115.25     189 1152.74   268.5 1176.78
   308.3  1185.5   328.2  1187.6   338.1  1187.2   348.1 1184.35   377.9 1168.46
   417.7 1153.52   437.6 1143.04   447.5 1136.06   467.4 1118.71   497.2 1089.51
   517.1 1067.28   527.1 1060.34     537 1058.99   539.4 1059.24   554.4 1060.75
   586.6 1062.99   606.5 1067.58   715.6 1111.43   755.3 1130.22     795 1151.82
   834.6 1175.14   864.4  1195.2   923.9 1243.43   973.5 1276.95  1102.5 1371.08
#Mann= 3 , 0 , 0
       0      .1       0   539.4    .045       0   554.4      .1       0
Bank Sta=539.4,554.4
XS Rating Curve= 0 ,0
Exp/Cntr=0.3,0.1

Type RM Length L Ch R = 1 ,553.7   ,551.4,553.7,555.6
XS GIS Cut Line= 3
     1943874.933       351031.14      1943662.42      350528.247
     1943458.744       350019.95
#Sta/Elev= 30
       0    1064    89.3 1070.72   148.9 1078.37   178.7 1083.21     268 1102.07
   307.7 1114.01   317.6 1117.57   347.4 1130.57   357.4 1130.84   367.3 1126.84
   377.2 1120.79   446.7 1075.11   456.6 1069.28   466.5 1064.86   486.4  1059.6
   506.2 1052.07   516.2 1049.27   526.1    1048   538.6 1048.23   553.6 1048.98
   585.8 1049.62   625.6 1055.38   655.5 1062.89   695.3 1076.16   774.9 1112.81
   844.6 1141.94   934.2  1181.6  1003.9 1217.96  1063.7 1254.08  1093.5 1271.19
#Mann= 3 , 0 , 0
       0      .1       0   538.6    .045       0   553.6      .1       0
Bank Sta=538.6,553.6
XS Rating Curve= 0 ,0
Exp/Cntr=0.3,0.1

Chan Stop Cuts=-1
Use User Specified Reach Order=0
Composite Channel Slope=5